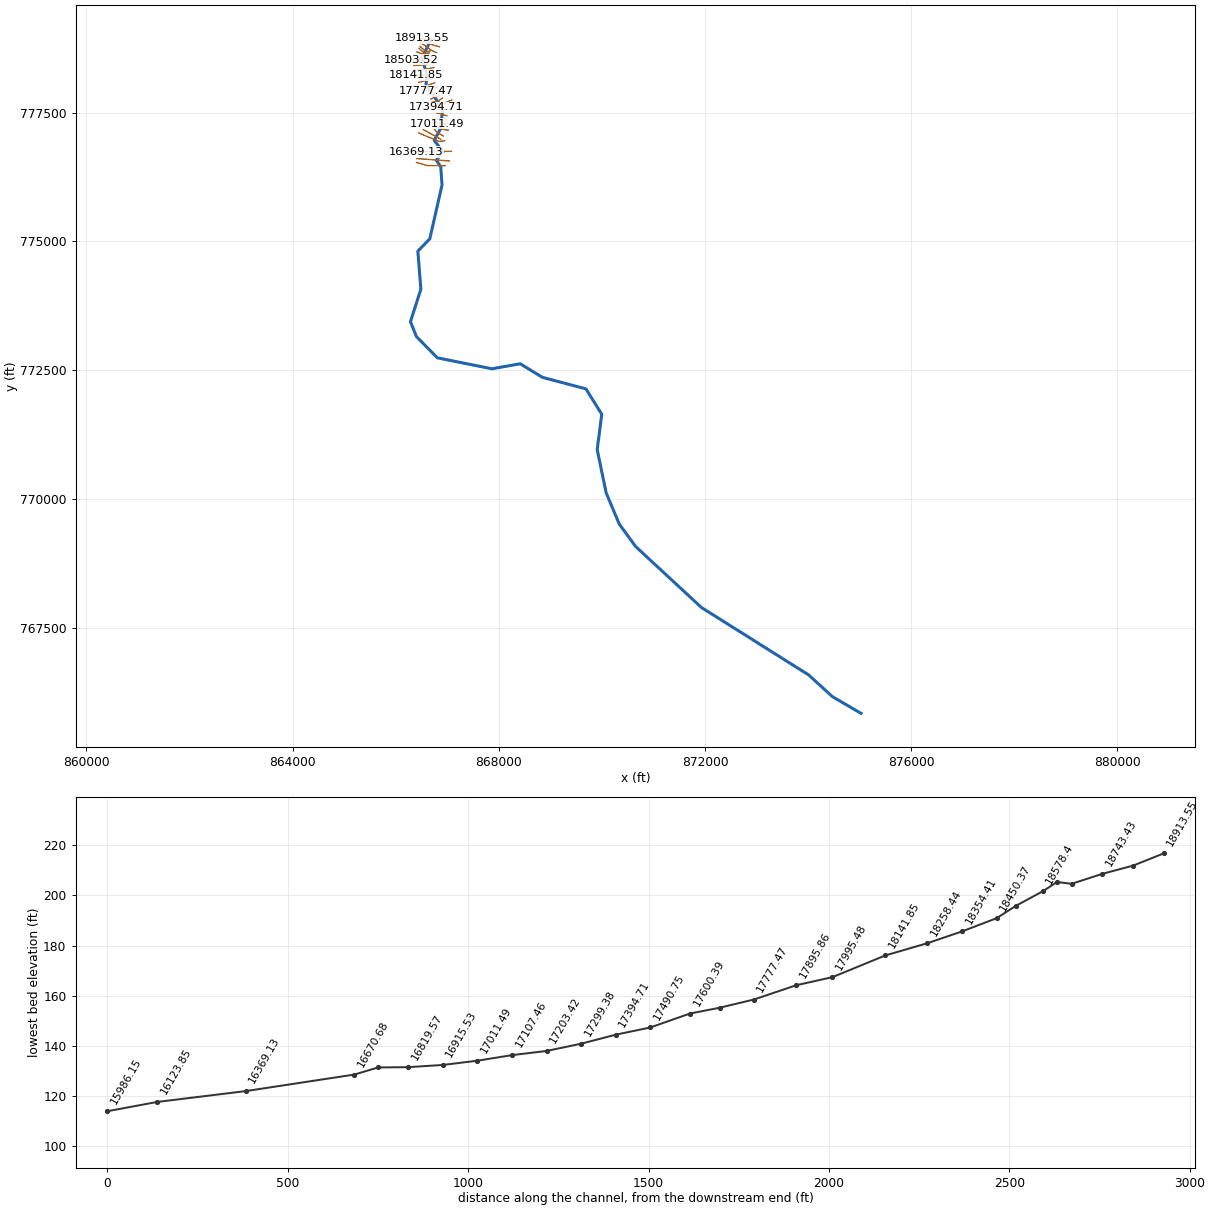
--- 9816_ras.prj (project) ---

Proj Title=9816
Current Plan=p01
Default Exp/Contr=0.3,0.1
English Units
Geom File=g01
Flow File=f01
Plan File=p01
Y Axis Title=Elevation
X Axis Title(PF)=Main Channel Distance
X Axis Title(XS)=Station
BEGIN DESCRIPTION:
RFD model 9816 exported to HEC-RAS
END DESCRIPTION:

--- 9816_ras.p01 (plan) ---

Plan Title=Plan 01
Program Version=4.10
Short Identifier=Plan 01
Geom File=g01
Flow File=f01
Subcritical Flow
Calc Critical at every XS
Secant Critical Depth

--- 9816_ras.f01 (steady flow) ---

Flow Title=Flow 01
Program Version=5.01
Number of Profiles= 6
Profile Names=10yr,25yr,50yr,100yr,100plus,500yr
River Rch & RM=9816,65,18913.55
  205.07  309.64  402.52  480.77  701.92 1118.28
River Rch & RM=9816,65,18828.49
  208.09  314.23  408.52  487.96  712.43 1132.75
River Rch & RM=9816,65,18743.43
   211.6  319.57  415.51  496.33  724.64 1149.55
River Rch & RM=9816,65,18658.36
   214.1  323.37  420.48  502.29  733.35 1161.48
River Rch & RM=9816,65,18503.52
   228.5  345.27  449.11  536.61  783.45  1229.8
River Rch & RM=9816,65,18354.41
  232.85  351.92  457.83  547.09  798.75  1250.7
River Rch & RM=9816,65,18258.44
  244.35  369.51  480.91  574.84  839.27 1305.78
River Rch & RM=9816,65,18141.85
  245.28  370.94  482.79  577.12  842.59 1310.32
River Rch & RM=9816,65,17995.48
     249  376.66  490.33  586.21  855.87 1328.45
River Rch & RM=9816,65,17895.86
  254.08  384.49  500.64  598.66  874.05 1353.23
River Rch & RM=9816,65,17777.47
  260.52   394.4  513.72  614.44  897.08  1384.5
River Rch & RM=9816,65,17682.68
   265.1  401.45  523.01  625.66  913.46 1406.67
River Rch & RM=9816,65,17490.75
  267.84  405.67  528.57  632.37  923.26 1419.91
River Rch & RM=9816,65,17394.71
  271.03  410.58  535.04  640.19  934.67 1435.29
River Rch & RM=9816,65,17203.42
  389.98  593.04  774.99  929.15 1356.56 1984.44
River Rch & RM=9816,65,17107.46
  393.34  598.22  781.83  937.41 1368.62 1999.86
River Rch & RM=9816,65,17011.49
  395.85   602.1  786.95   943.6 1377.66 2011.39
River Rch & RM=9816,65,16915.53
  400.46   609.2  796.32  954.92 1394.19 2032.47
River Rch & RM=9816,65,16819.57
  644.59  985.07 1292.02    1553 2267.38 3100.61
River Rch & RM=9816,65,16670.68
  648.66  991.39  1300.4 1563.16 2282.21 3118.41
River Rch & RM=9816,65,16369.13
  668.56 1022.61 1342.08    1614 2356.44 3208.44
River Rch & RM=9816,65,15986.15
  671.71 1027.57 1348.72 1622.11 2368.28 3222.81
River Rch & RM=9816,65,15814.06
  676.27 1034.74  1358.3 1633.81 2385.36 3243.53
River Rch & RM=9816,65,15517.13
  694.42 1063.29 1396.49 1680.44 2453.45  3325.9
River Rch & RM=9816,65,15242.19
  831.85 1278.02 1682.47 2028.38 2961.44 3924.89
River Rch & RM=9816,65,15026.04
   836.8 1285.84 1692.95 2041.22 2980.18 3947.02
River Rch & RM=9816,65, 14809.9
  845.86 1300.23 1712.31 2064.97 3014.86  3988.2
River Rch & RM=9816,65,14514.57
  852.36 1310.53 1726.15 2081.95 3039.64 4017.51
River Rch & RM=9816,65,14179.21
  867.37 1334.26 1758.01 2120.98 3096.63 4084.62
River Rch & RM=9816,65,13945.31
 1029.82  1591.1 2102.74 2543.21 3713.09  4799.5
River Rch & RM=9816,65,13640.94
 1037.48  1603.3 2119.18 2563.42  3742.6 4833.57
River Rch & RM=9816,65,13461.08
 1045.42 1615.94 2136.23 2584.39 3773.21 4868.91
River Rch & RM=9816,65,13210.85
  1048.4 1620.72 2142.69 2592.37 3784.86 4882.47
River Rch & RM=9816,65,13138.79
 1049.29 1622.15 2144.63 2594.76 3788.35 4886.54
River Rch & RM=9816,65,12756.63
 1119.92 1734.98 2297.09 2782.57 4062.55  5202.4
River Rch & RM=9816,65,12690.05
 1133.73  1757.1 2327.03 2819.51 4116.49  5264.4
River Rch & RM=9816,65,12319.55
 1140.46 1767.89 2341.64 2837.55 4142.82 5294.64
River Rch & RM=9816,65,12216.18
 1142.51 1771.17 2346.08 2843.03 4150.82 5303.83
River Rch & RM=9816,65,11854.27
 1164.35 1806.19 2393.52 2901.59 4236.32 5401.89
River Rch & RM=9816,65,11442.97
 1189.94 1847.19 2449.02 2970.08 4336.31 5516.07
River Rch & RM=9816,65,11297.13
 1224.92 1903.36 2525.18 3064.19 4473.71 5672.84
River Rch & RM=9816,65,10774.09
 1381.78 2152.92 2861.62 3477.74 5077.51 6345.14
River Rch & RM=9816,65,10717.28
 1384.85 2157.85  2868.3    3486 5089.56 6358.59
River Rch & RM=9816,65,10222.76
 1403.04    2187 2907.79 3534.74 5160.72 6437.83
River Rch & RM=9816,65,9746.634
 1590.99 2485.91 3310.75 4029.96 5883.75 7225.61
River Rch & RM=9816,65,9644.439
 1593.72 2490.28 3316.67 4037.26  5894.4 7237.23
River Rch & RM=9816,65,8854.747
 1619.39 2531.36 3372.26 4105.83 5994.51 7346.08
River Rch & RM=9816,65,8325.091
 1730.03 2708.55 3612.24 4401.92  6426.8 7813.72
River Rch & RM=9816,65,7757.907
  1738.3 2721.82 3630.21 4424.11 6459.21 7848.63
River Rch & RM=9816,65, 7619.66
  1739.1 2723.09 3631.95 4426.25 6462.33    7852
River Rch & RM=9816,65, 7393.09
  1750.8 2741.86 3657.39 4457.68 6508.21 7901.43
River Rch & RM=9816,65,7301.544
 1753.45 2746.12 3663.16 4464.81 6518.62 7912.65
River Rch & RM=9816,65,6625.828
 1939.13 3044.59 4068.37  4965.8 7250.07 8696.18
River Rch & RM=9816,65,6156.863
  1964.4  3085.2  4123.5 5033.97 7349.59 8801.83
River Rch & RM=9816,65,5687.897
 1970.51 3095.05  4136.9 5050.56 7373.81 8827.63
River Rch & RM=9816,65,4995.762
 1972.01 3097.48 4140.21 5054.67 7379.82 8834.08
Boundary for River Rch & Prof#=9816,65,1
Up Type= 0
Dn Type= 2
Boundary for River Rch & Prof#=9816,65,2
Up Type= 0
Dn Type= 2
Boundary for River Rch & Prof#=9816,65,2
Up Type= 0
Dn Type= 2
Boundary for River Rch & Prof#=9816,65,2
Up Type= 0
Dn Type= 2
Boundary for River Rch & Prof#=9816,65,2
Up Type= 0
Dn Type= 2
Boundary for River Rch & Prof#=9816,65,2
Up Type= 0
Dn Type= 2

--- 9816_ras.g01 (geometry) ---

Geom Title=9816
Program Version=4.10

River Reach=9816,65
Reach XY= 30
866684.355488619778910.628440458866505.299040101778555.004682199
866610.684989493778226.286171322 866586.54723207778031.806443449
866911.692336172777582.642556287866872.155462342 777190.69528703
866747.797018321776959.741960508866918.822572078776739.549097825
866787.875792572776577.603687721866874.030575783776445.480009869
866899.282968357776095.064937578866661.618265066775050.277654633
866430.224638187774812.181550296866488.626229716774073.376547851
866286.305208654773442.987935111866404.027400125773152.238090697
 866808.68535762 772742.33489336867869.111288354772529.964318893
868414.701729736772627.591357868868847.824391004772363.019076185
869690.436752942772140.290857836869997.238986213771646.969325279
869908.867915425 770961.72326174870082.257431985770125.483233583
870335.646360042769519.337921143870654.295352464769082.673740214
871929.236260942767900.405745817874011.554656912766590.701605286
874469.832187133766171.481883213 875026.93986095765845.832032735

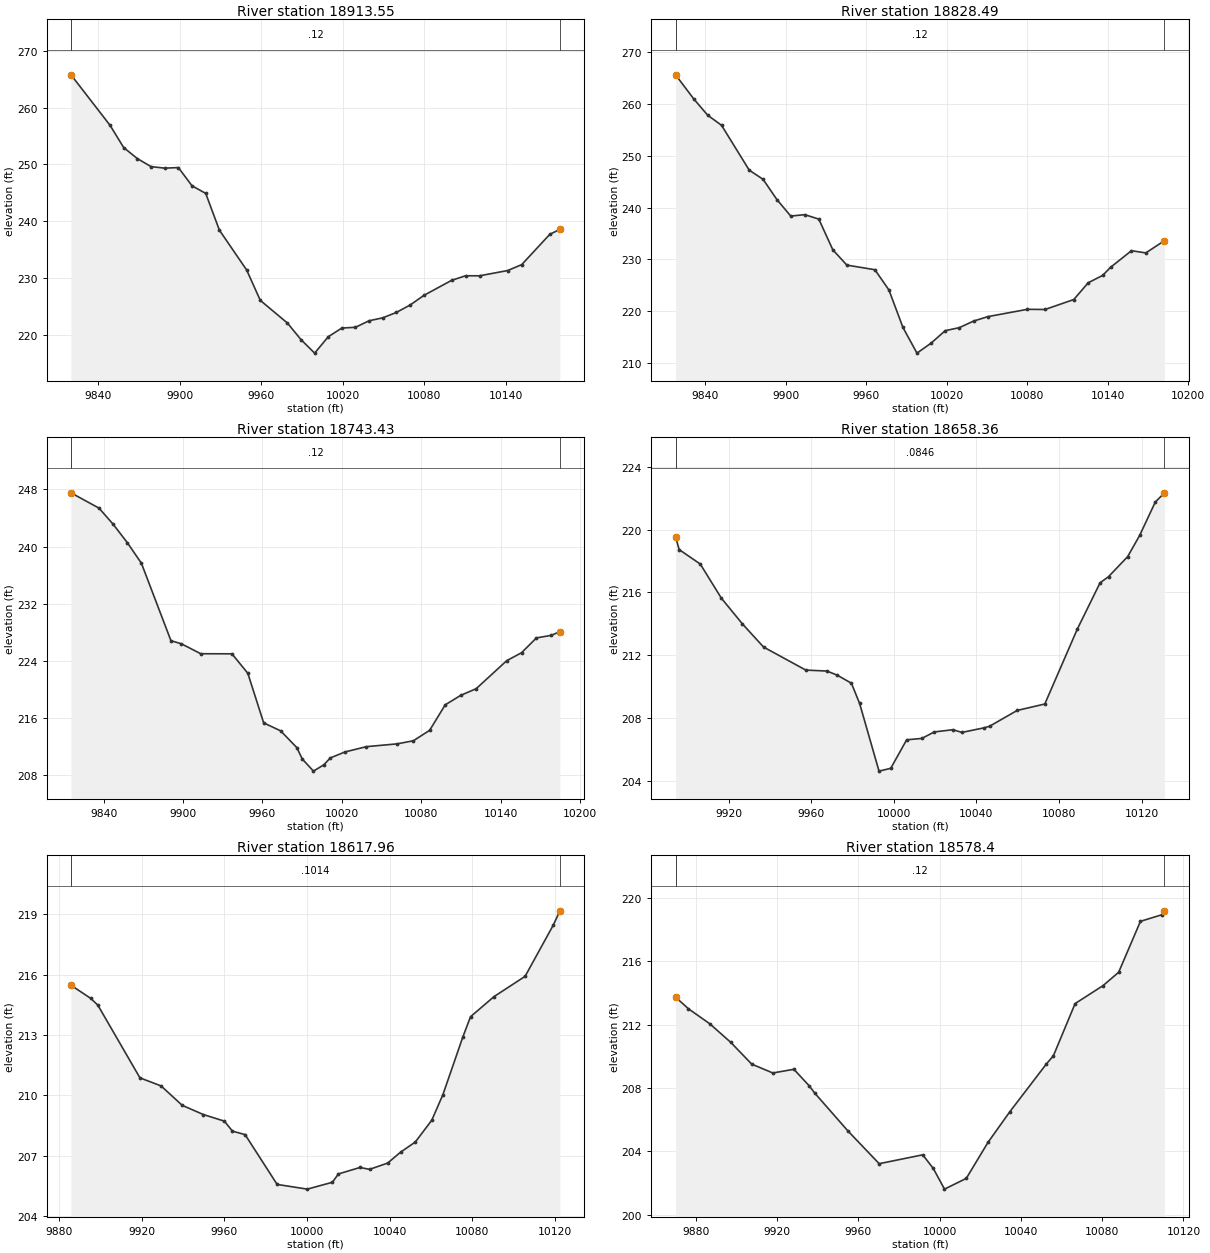
Type RM Length L Ch R = 1 ,18913.55,85.061900,85.061900,85.061900
XS GIS Cut Line= 6
866863.547651244778895.035375137866739.207999005778909.145035195
866662.647036521778909.010495324866629.606235222778911.433370597
866579.252107458778920.440370688866507.889458438778939.488393113
#Sta/Elev= 30
9820.042265.82189848.773256.92249858.837252.98869868.902 251.0389878.966249.6292
 9889.03249.35279899.094249.45689909.158246.23839919.223244.90119929.287238.4162
9949.391231.37219959.398226.02679979.413222.01329989.419219.08099999.425216.7142
10009.43 219.60510019.44221.139210029.46221.274310039.48222.423510049.51 222.941
 10059.6223.896510069.76 225.21310079.92 226.91510100.23 229.55710110.47230.3615
10120.82230.359910141.52231.286610151.87232.333310172.57237.690210179.93238.5436
#Mann= 3 , 0 , 0
9820.042    0.12       09820.042    0.12       010179.93    0.12       0
#XS Ineff= 2 , 0
       0                               0
Bank Sta=9820.042,10179.93
Exp/Cntr=0.3,0.1

Type RM Length L Ch R = 1 ,18828.49,85.061900,85.061900,85.061900
XS GIS Cut Line= 6
 866848.17663255778776.654689952 866764.29763139778798.177114877
866671.876582771 778826.36864219866660.680637159778829.897477857
866597.325624444778852.393765092866502.069826085778889.591072454
#Sta/Elev= 30
9817.779265.65939831.382260.98229841.706257.8544 9852.03 255.9019872.678247.2293
9883.002245.45449893.326241.5349 9903.65238.34469914.095238.6194 9924.55237.7602
9935.005231.8239 9945.46228.8654 9966.37227.96799976.825224.05279987.279216.8044
9997.734211.842210008.21213.763710018.77216.178510029.38216.776310039.99218.0467
 10050.6218.901110079.97220.3118 10093.2220.280510114.63222.205110125.41 225.452
10136.14226.867410142.12228.449810157.61231.645810168.35 231.22410182.23233.5888
#Mann= 3 , 0 , 0
9817.779    0.12       09817.779    0.12       010182.23    0.12       0
#XS Ineff= 2 , 0
       0                               0
Bank Sta=9817.779,10182.23
Exp/Cntr=0.3,0.1

Type RM Length L Ch R = 1 ,18743.43,85.061900,85.061900,85.061900
XS GIS Cut Line= 6
866794.823824731778662.745811786866741.826142627778682.679655731
866699.041073606 778704.85262164866661.166301968778730.002836443
866563.813351908778804.048062456866479.214162166778851.294303421
#Sta/Elev= 30
9815.235247.52089836.414245.38029847.098243.13029857.782240.55869868.466237.6703
9890.809226.82659898.633226.39979913.335225.00199936.901224.99049948.905 222.272
9960.909215.32319973.704214.21359985.912211.87319990.098210.27059998.531208.5727
10006.33209.4509 10011.3210.422510022.46211.261610038.59211.997810061.83212.3894
10074.11212.824210086.39214.288110098.15217.851210109.84219.174510121.53220.1073
10144.65 224.03110155.87225.1474 10167.1227.217710178.32227.572310184.81228.1021
#Mann= 3 , 0 , 0
9815.235    0.12       09815.235    0.12       010184.81    0.12       0
#XS Ineff= 2 , 0
       0                 10041.2       0
Bank Sta=9815.235,10184.81
Exp/Cntr=0.3,0.1

Type RM Length L Ch R = 1 ,18658.36,40.401800,40.401800,40.401800
XS GIS Cut Line= 3
866666.697130356778693.743293105866590.186385781778677.744990627
866471.692478528778782.975295876
#Sta/Elev= 29
9894.378219.55559896.112218.73679906.328217.81599916.544 215.637 9926.76213.9922
9936.977212.51979957.409211.05169967.625210.98979972.543210.7329 9979.48210.2151
9983.469208.92029992.854204.60629998.529204.785810006.23206.603810013.59206.6926
 10019.6207.106110028.65207.248210032.98207.075310043.71 207.36810046.35207.4673
10059.72208.4767 10073.1 208.88710088.89213.681410099.85216.615710103.95217.0103
10113.22218.289410119.01219.638910126.59221.770510131.02222.3576
#Mann= 3 , 0 , 0
9894.378  0.0846       09894.378  0.0846       010131.02  0.0846       0
#XS Ineff= 2 , 0
       09978.643        10050.65       0
Bank Sta=9894.378,10131.02
Exp/Cntr=0.3,0.1

Type RM Length L Ch R = 1 ,18617.96,39.560900,39.560900,39.560900
XS GIS Cut Line= 3
866647.678064636778656.942033416866571.167271022778640.943744871
 866452.67332697778746.174145855
#Sta/Elev= 27
9885.696215.46949895.185214.82059898.648214.48649919.081 210.8629929.297210.4618
9939.513209.4977 9949.73209.03989959.946208.70919963.862208.2123 9969.97208.0405
9985.484205.562210000.09205.328310012.23205.669210015.15206.083710025.61206.4058
10030.21206.311610038.98206.623710045.27207.169610052.35207.669510060.33208.7532
10065.73210.027610075.39212.8992 10079.1213.902510090.45214.902110105.51215.9113
10119.22218.471710122.34219.1701
#Mann= 3 , 0 , 0
9885.696  0.1014       09885.696  0.1014       010122.34  0.1014       0
#XS Ineff= 2 , 0
       09982.409        10054.59       0
Bank Sta=9885.696,10122.34
Exp/Cntr=0.3,0.1

Type RM Length L Ch R = 1 , 18578.4,74.881100,74.881100,74.881100
XS GIS Cut Line= 3
866641.125603656778642.487435558866559.356301989778619.911333763
866413.964083076778675.849784377
#Sta/Elev= 25
 9870.02  213.739876.375212.99529886.749212.06159897.123210.88669907.497209.5069
9917.872208.94769928.246209.18069935.728208.1468 9938.62207.66389954.849205.2909
9970.231203.2259 9991.66203.78569996.869202.923510002.37201.621610013.09202.2985
 10023.8204.574110034.52206.501110052.57209.525710055.95210.026910066.66213.3252
10080.42214.459110088.09215.300810098.81218.512410109.52218.935110110.63219.1753
#Mann= 3 , 0 , 0
 9870.02    0.12       0 9870.02    0.12       010110.63    0.12       0
#XS Ineff= 2 , 0
       09981.288        10041.73       0
Bank Sta=9870.02,10110.63
Exp/Cntr=0.3,0.1

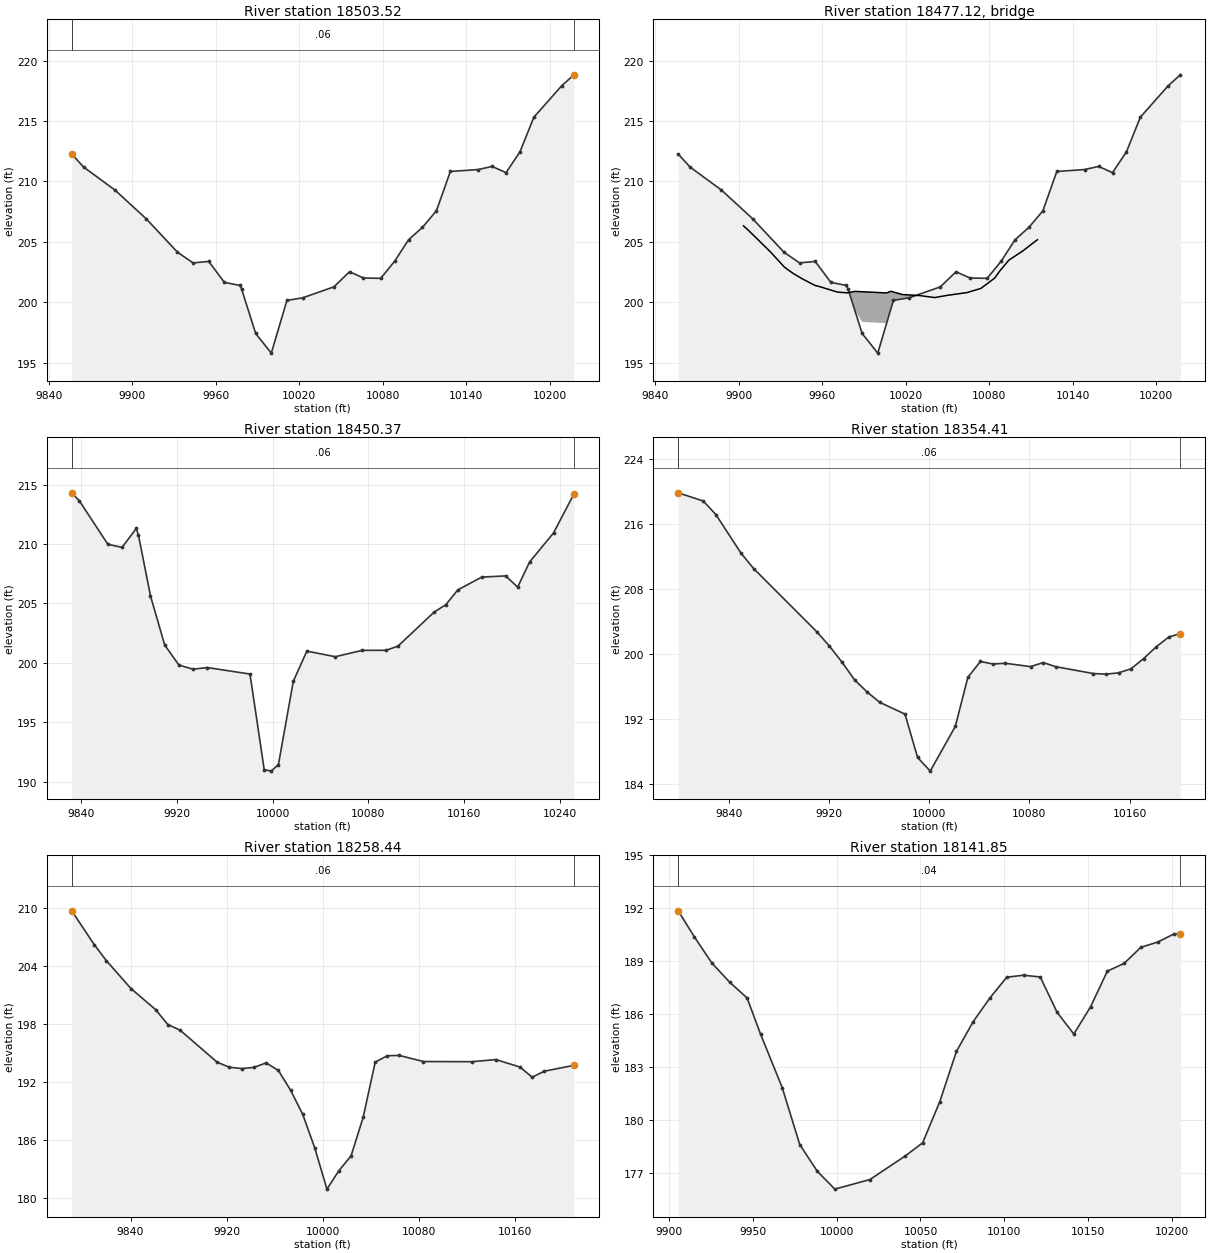
Type RM Length L Ch R = 1 ,18503.52,53.151800,53.151800,53.151800
XS GIS Cut Line= 3
 866632.58437479778630.650414831866435.568822218778529.624013446
866296.320598145778523.915198698
#Sta/Elev= 30
9856.596212.26429865.119 211.1889887.595209.29329910.072206.91499932.548204.1535
9943.786203.26489955.024203.38829966.262201.6553  9977.5201.40329978.558201.1303
9988.738197.43229999.976195.806110011.21200.167110022.45200.375710044.93201.2847
10056.17 202.53210066.22202.020510078.57201.987710088.58203.396510098.59205.1759
 10108.6206.205410118.61 207.57110128.62 210.82410148.63210.985210158.64211.2425
10168.65210.728610178.66212.450310188.67215.316510208.68217.914210217.37218.8155
#Mann= 3 , 0 , 0
9856.596    0.06       09856.596    0.06       010217.37    0.06       0
#XS Ineff= 2 , 0
       09983.676        10009.85       0
Bank Sta=9856.596,10217.37
Exp/Cntr=0.3,0.1

Type RM Length L Ch R = 3 ,18477.12,,,
BEGIN DESCRIPTION:
END DESCRIPTION:
Bridge Culvert--1,0,-1,-1, 0
Deck Dist Width WeirC Skew NumUp NumDn MinLoCord MaxHiCord MaxSubmerge Is_Ogee
14.575900,24.000000,2.6,0, 38, 38, , , 0.95, 0, 0,0,,
 9903.50 9906.61 9907.20 9919.98 9922.66 9932.77 9938.71 9945.55 9954.77 9958.33
 9970.82 9971.12 9978.18 9981.76 9981.76 9983.32 9989.17 9994.8110006.3010009.48
10011.7610011.7610017.7910029.2810029.2810029.7810040.8210049.8110052.3610063.90
10063.9710073.9910084.0710087.5110094.1510104.2310114.3110114.67
  206.33  206.00  205.94  204.50  204.20  202.93  202.43  201.96  201.41  201.30
  200.86  200.85  200.79  200.87  200.87  200.91  200.88  200.85  200.78  200.92
  200.84  200.84  200.65  200.57  200.57  200.57  200.40  200.58  200.62  200.81
  200.81  201.15  202.02  202.58  203.49  204.26  205.15  205.18
 -793.67 -794.00 -794.06 -795.50 -795.80 -797.07 -797.57 -798.04 -798.59 -798.70
 -799.14 -799.15 -799.21 -799.13  198.37  198.41  198.38  198.35  198.28  198.42
  198.34 -799.16 -799.35 -799.43 -799.43 -799.43 -799.60 -799.42 -799.38 -799.19
 -799.19 -798.85 -797.98 -797.42 -796.51 -795.74 -794.85 -794.82
 9903.50 9906.61 9907.20 9919.98 9922.66 9932.77 9938.71 9945.55 9954.77 9958.33
 9970.82 9971.12 9978.18 9983.32 9984.79 9984.79 9989.17 9994.8110006.3010009.48
10014.7910014.7910017.7910029.2810029.2810029.7810040.8210049.8110052.3610063.90
10063.9710073.9910084.0710087.5110094.1510104.2310114.3110114.67
  206.33  206.00  205.94  204.50  204.20  202.93  202.43  201.96  201.41  201.30
  200.86  200.85  200.79  200.91  200.90  200.90  200.88  200.85  200.78  200.92
  200.75  200.75  200.65  200.57  200.57  200.57  200.40  200.58  200.62  200.81
  200.81  201.15  202.02  202.58  203.49  204.26  205.15  205.18
 -793.67 -794.00 -794.06 -795.50 -795.80 -797.07 -797.57 -798.04 -798.59 -798.70
 -799.14 -799.15 -799.21 -799.09 -799.10  198.40  198.38  198.35  198.28  198.42
  198.25 -799.25 -799.35 -799.43 -799.43 -799.43 -799.60 -799.42 -799.38 -799.19
 -799.19 -798.85 -797.98 -797.42 -796.51 -795.74 -794.85 -794.82
BR Coef=-1 , 0 , 0 ,, 0 ,,,0.8,0,1,0,
WSPro=,,,, 1 ,,,, 0 ,,,, 0 ,,,,-1 ,-1 ,-1 , 0 , 0 , 0 , 0 , 0
BC Design=,, 0 ,, 0 ,,,,,,

Type RM Length L Ch R = 1 ,18450.37,95.961600,95.961600,95.961600
XS GIS Cut Line= 3
866660.390166322778605.156878429866461.731680551 778477.49745902
866278.000327473778475.307496767
#Sta/Elev= 30
9831.995214.30819838.402213.62629862.176209.97959874.062209.71849885.949211.3103
9887.778  210.749897.836205.63329909.723201.50729921.609199.81599933.496199.4722
9945.383199.61069981.043199.0632 9992.93191.02829998.764190.898410004.82191.4519
10017.26198.451910028.59 200.99510052.36200.522310074.87201.057810094.87201.0618
10104.87 201.41910134.87204.257810144.87204.906510154.87206.142310174.87207.2211
10194.88207.319410204.88206.376110214.88208.489110234.88210.931110251.88214.1997
#Mann= 3 , 0 , 0
9831.995    0.06       09831.995    0.06       010251.88    0.06       0
#XS Ineff= 2 , 0
       09986.353        10013.23       0
Bank Sta=9831.995,10251.88
Exp/Cntr=0.3,0.1

Type RM Length L Ch R = 1 ,18354.41,95.961600,95.961600,95.961600
XS GIS Cut Line= 6
866754.884382867778449.542359108866556.735280647778426.521672803
866554.758206136778426.219718537866551.047303546778425.754041862
866506.851932151778423.638733399866355.828498915778411.484497325
#Sta/Elev= 30
9799.518219.80929819.536218.80359829.604217.13649849.738212.38089859.805 210.501
9910.142202.75519920.209200.99579930.276199.02359940.343 196.8419950.411195.3436
9960.478194.07999980.612192.6326 9990.68187.310510000.76185.631210020.81191.1237
10030.82197.142410040.83199.099110050.84198.786110060.88198.874810080.94198.4631
10090.97 198.96310101.01198.4571 10131.1197.615410141.13197.537610151.17197.7031
 10161.2198.202110171.23199.457910181.26200.8951 10191.3202.1013 10200.5202.5315
#Mann= 3 , 0 , 0
9799.518    0.06       09799.518    0.06       0 10200.5    0.06       0
#XS Ineff= 2 , 0
       0                               0
Bank Sta=9799.518,10200.5
Exp/Cntr=0.3,0.1

Type RM Length L Ch R = 1 ,18258.44,116.592500,116.592500,116.592500
XS GIS Cut Line= 5
866743.273027933778373.863987114 866564.42259375778336.180230467
866539.424066817778333.365135301 866537.42457747778333.319942942
866330.433606465778313.153161603
#Sta/Elev= 30
9791.066209.6711 9809.74206.1877 9819.96204.51099840.399201.63989860.838199.4763
9871.058197.92259881.277197.34669911.936194.05619922.156193.52259932.375193.3894
9942.595193.49999952.814193.97289963.034193.18829973.253191.14089983.326188.6489
9993.389185.168610003.44180.938710013.48182.855410023.53184.365910033.58188.3408
10043.63194.046410053.67194.711210063.72194.739410083.81194.1112   10124194.0945
 10144.1194.313210164.19193.540110174.24 192.49410184.29193.111510208.97193.7187
#Mann= 3 , 0 , 0
9791.066    0.06       09791.066    0.06       010208.97    0.06       0
#XS Ineff= 2 , 0
       0                               0
Bank Sta=9791.066,10208.97
Exp/Cntr=0.3,0.1

Type RM Length L Ch R = 1 ,18141.85,146.369100,146.369100,146.369100
XS GIS Cut Line= 3
866694.221294643778269.600358451866551.017107837778225.048196253
866401.468985508778227.628613369
#Sta/Elev= 29
9905.483191.85469915.141190.37219925.613188.88549936.086187.81369946.559186.9093
9954.632184.85069967.505181.82929977.977178.5938 9988.45 177.0769998.923176.0633
10019.87176.609110040.81177.937910051.29178.689810061.48 181.01510071.48183.8812
10081.48185.570610091.48186.917410101.48188.087210111.48188.201410121.48188.1018
10131.49186.099810141.49184.864210151.49186.407710161.49188.431210171.49188.8703
10181.49189.7841 10191.5190.0805 10201.5190.553410205.03190.5517
#Mann= 3 , 0 , 0
9905.483    0.04       09905.483    0.04       010205.03    0.04       0
#XS Ineff= 2 , 0
       0                               0
Bank Sta=9905.483,10205.03
Exp/Cntr=0.3,0.1

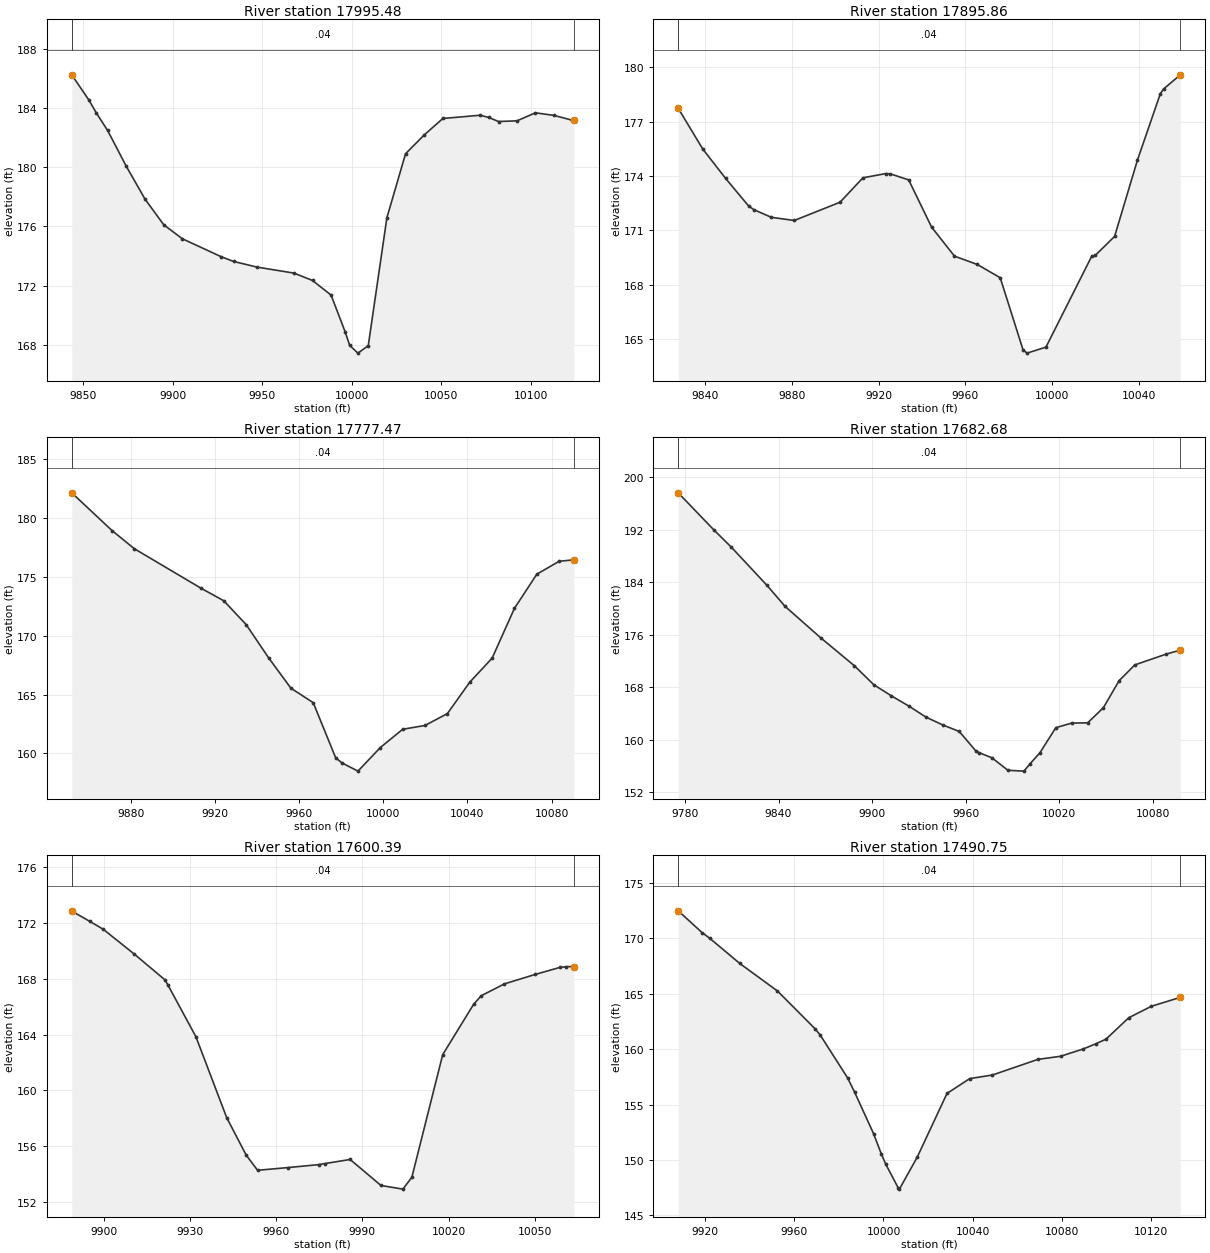
Type RM Length L Ch R = 1 ,17995.48,99.621000,99.621000,99.621000
XS GIS Cut Line= 6
866714.182606352778158.958813901 866627.63848305 778133.04540907
866589.453731008778122.930602065866565.458272066778116.431362107
866504.183230459778098.539378972866444.230258353 778083.23492855
#Sta/Elev= 30
9843.685186.2577 9853.27184.54789857.486183.66179863.709182.49159874.147180.0645
9884.586177.84859895.025176.11489905.463175.16269927.211173.94489934.025173.6302
  9947.1173.24779967.789172.83969978.143172.34069988.508171.35299996.387168.8605
9998.865 167.95610003.49167.424510009.28167.9273 10019.7176.594810030.12180.9191
10040.54  182.1910050.95183.3039 10071.7183.522610076.53183.375210082.02183.0985
10092.34 183.14410102.66183.687510112.98183.5131 10123.3183.1816 10124.1183.2272
#Mann= 3 , 0 , 0
9843.685    0.04       09843.685    0.04       0 10124.1    0.04       0
#XS Ineff= 2 , 0
       0                               0
Bank Sta=9843.685,10124.1
Exp/Cntr=0.3,0.1

Type RM Length L Ch R = 1 ,17895.86,118.393800,118.393800,118.393800
XS GIS Cut Line= 2
866755.709575059778076.065508618866536.283831613778002.558699345
#Sta/Elev= 26
9827.652177.72899838.947175.48629849.493173.86299860.039172.34919862.488172.1392
9870.585 171.7179881.132171.54269902.224172.5489 9912.77173.89689923.316174.1295
9925.451174.11279933.863 173.7829944.409171.17949954.955169.57759965.501169.1148
9976.047 168.3849986.594164.39949988.414 164.225 9997.14164.556110018.23169.5704
 10019.9169.619210028.78170.665110039.32174.880510049.87178.543610051.38178.8002
10059.06179.5776
#Mann= 3 , 0 , 0
9827.652    0.04       09827.652    0.04       010059.06    0.04       0
#XS Ineff= 2 , 0
       0                               0
Bank Sta=9827.652,10059.06
Exp/Cntr=0.3,0.1

Type RM Length L Ch R = 1 ,17777.47,94.793200,94.793200,94.793200
XS GIS Cut Line= 2
 866823.00216563777998.382878223866598.443479736777917.683227268
#Sta/Elev= 22
9851.991182.1225 9871.12178.92019881.746177.37579913.625174.00279924.251172.9591
9934.877170.93519945.503168.12729956.129165.54019966.755164.30789977.381159.6438
9980.269159.21139988.008158.49839998.634160.499410009.26162.050610019.89162.3755
10030.51163.384310041.14166.046710051.76168.086110062.39172.319110073.02175.2166
10083.64176.312810090.61176.4359
#Mann= 3 , 0 , 0
9851.991    0.04       09851.991    0.04       010090.61    0.04       0
#XS Ineff= 2 , 0
       0                               0
Bank Sta=9851.991,10090.61
Exp/Cntr=0.3,0.1

Type RM Length L Ch R = 1 ,17682.68,82.283700,82.283700,82.283700
XS GIS Cut Line= 6
866904.766508313777949.809646806866800.766382118777892.010273435
866765.739004244777874.739788697866733.049888183777862.819501824
866674.344553205777849.917320201866605.910321031777842.877381397
#Sta/Elev= 28
9775.735197.63059798.349192.0341 9809.79189.34799832.671183.52339844.111180.3542
9866.993175.55779888.563171.30169901.146168.38029912.296166.71169923.445165.1589
9934.558163.45319945.202162.27839955.846161.2756 9966.49158.30629968.566158.0446
9976.813157.26289987.059155.35659997.305155.2331   10001156.295210007.53158.0228
10017.77161.8575   10028162.555710038.12162.584410048.22164.892910058.33169.0208
10068.38 171.41610088.42173.057310097.53173.6654
#Mann= 3 , 0 , 0
9775.735    0.04       09775.735    0.04       010097.53    0.04       0
#XS Ineff= 2 , 0
       0                               0
Bank Sta=9775.735,10097.53
Exp/Cntr=0.3,0.1

Type RM Length L Ch R = 1 ,17600.39,109.639600,109.639600,109.639600
XS GIS Cut Line= 2
866845.226838768777827.268886417866682.491496647777763.174915731
#Sta/Elev= 26
9888.757172.87839889.001172.82999894.949172.13399899.749171.55199910.496169.7833
9921.244 167.9219922.237167.56269931.992163.85289942.739158.03859949.526155.3554
9953.487154.26899964.235 154.4669974.982154.67989976.814154.7457 9985.73155.0446
9996.478153.1782 10004.1152.917110007.23153.765110017.97162.558810028.72166.1657
10031.39166.786410039.47167.638710050.22168.317410058.68168.813710060.96168.8706
10063.66168.8842
#Mann= 3 , 0 , 0
9888.757    0.04       09888.757    0.04       010063.66    0.04       0
#XS Ineff= 2 , 0
       0                               0
Bank Sta=9888.757,10063.66
Exp/Cntr=0.3,0.1

Type RM Length L Ch R = 1 ,17490.75,96.039700,96.039700,96.039700
XS GIS Cut Line= 6
866906.423743951777781.344304156866847.933694762  777738.4282536
 866832.04783716 777728.84036699866830.321737311777727.830129791
866818.075788555777720.669014099866702.303557023777697.635500199
#Sta/Elev= 26
9907.899172.46949918.624170.50189922.068169.98939935.528167.72229952.432165.2409
9969.336161.82729971.681161.25159983.872157.4151 9987.08 156.1089995.552 152.381
    9999 150.568   10001149.637710006.61147.492310007.16147.373710015.19150.2688
10028.52156.003210038.71157.339510048.91157.6641 10069.3159.0722 10079.5159.3536
10089.69160.016510095.49 160.49310099.89160.900310110.09162.829410120.28163.8652
10133.23164.6657
#Mann= 3 , 0 , 0
9907.899    0.04       09907.899    0.04       010133.23    0.04       0
#XS Ineff= 2 , 0
       0                               0
Bank Sta=9907.899,10133.23
Exp/Cntr=0.3,0.1

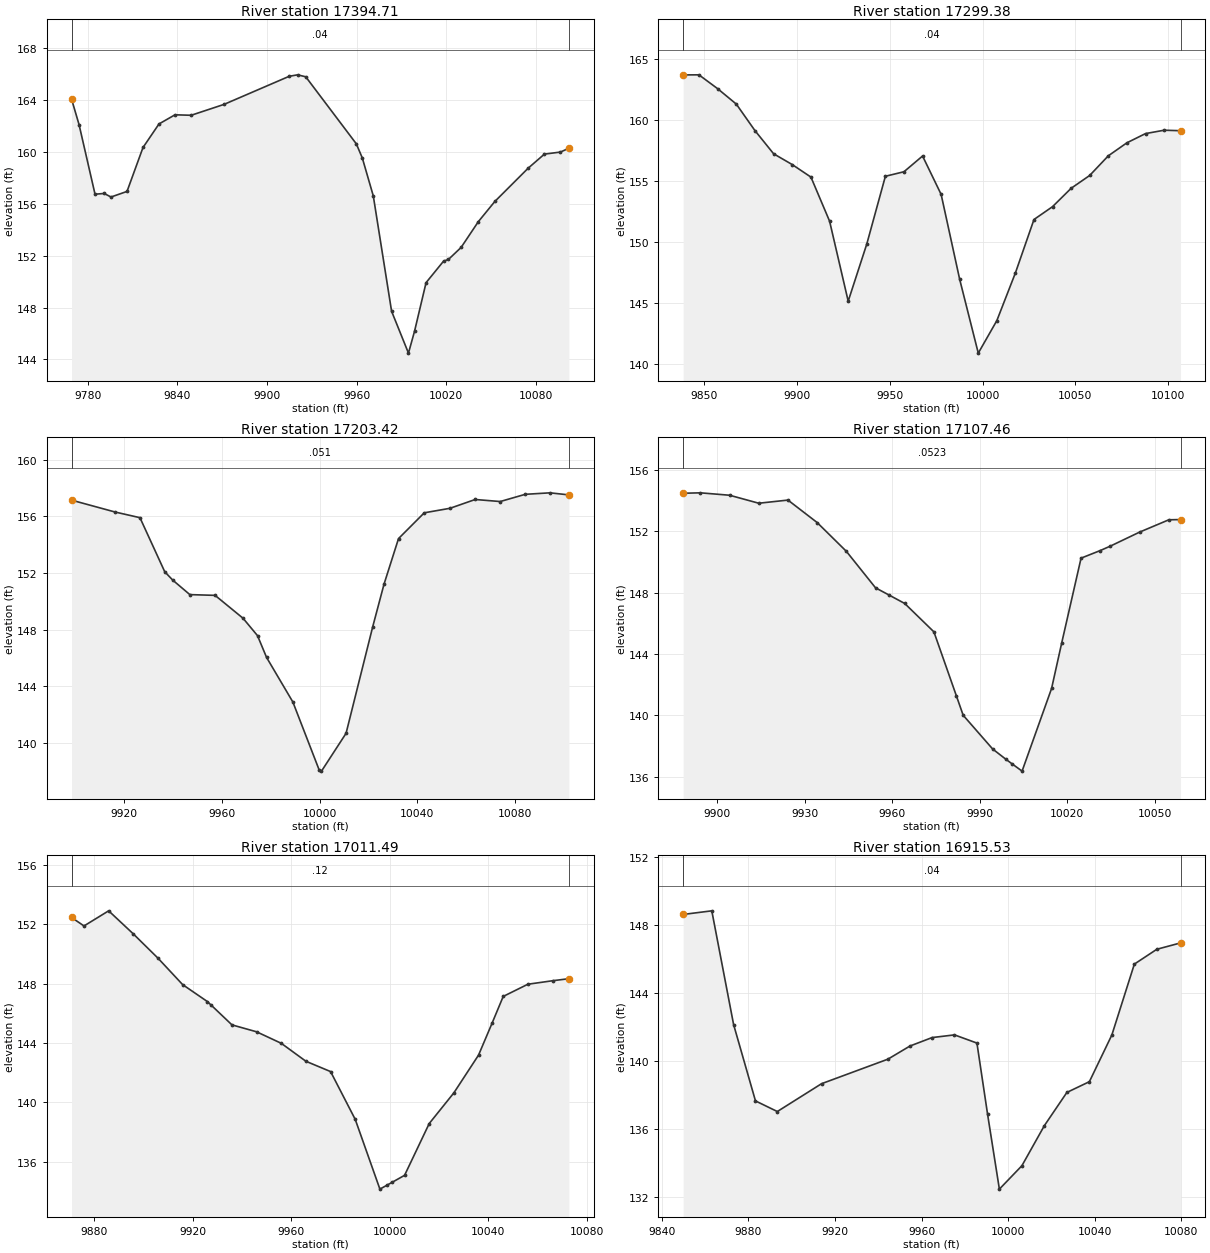
Type RM Length L Ch R = 1 ,17394.71,95.333000,95.333000,95.333000
XS GIS Cut Line= 6
867089.687994004777742.809947089867020.243029114777716.231156936
866948.412224075777684.348004174866906.641660872777662.484893918
866850.180996355777627.602339962866789.758241219777599.908168396
#Sta/Elev= 30
9769.145164.07979774.165162.11269784.872156.74279790.994156.79889795.579156.5258
9806.287156.95629816.994 160.3439827.702162.15839838.409162.86339849.239162.8266
9871.186163.66319914.884165.83179920.484165.94469925.943165.79349959.804160.6253
9963.814159.5352 9971.17156.60889983.419147.71849994.717144.49129998.777146.1767
 10006.5149.924810018.23151.584110021.45151.709210029.95152.638410041.48154.6237
10052.54156.182310074.85158.747510085.72159.831910096.48159.991210102.12 160.286
#Mann= 3 , 0 , 0
9769.145    0.04       09769.145    0.04       010102.12    0.04       0
#XS Ineff= 2 , 0
       09926.801                       0
Bank Sta=9769.145,10102.12
Exp/Cntr=0.3,0.1

Type RM Length L Ch R = 1 ,17299.38,95.961600,95.961600,95.961600
XS GIS Cut Line= 6
867073.404640751777570.458828448867054.574925821777567.915220316
 866994.74552714777561.921869393866949.415895733 777559.22348572
866857.730069058777556.994126279866806.234512734777552.771091425
#Sta/Elev= 28
9838.683163.71769847.164163.72499857.255162.58849867.307 161.3269877.357 159.152
9887.407157.25539897.457156.36879907.507155.34519917.557151.73219927.576 145.179
9937.593149.86169947.611155.41329957.629155.78399967.641157.07269977.645153.9279
9987.649146.95729997.654140.921910007.66143.587310017.66 147.49510027.66151.8708
10037.66152.922710047.67154.426910057.67155.4782 10067.7157.088410077.72158.1551
10087.75158.910610097.78 159.18610106.62159.1465
#Mann= 3 , 0 , 0
9838.683    0.04       09838.683    0.04       010106.62    0.04       0
#XS Ineff= 2 , 0
       09967.849                       0
Bank Sta=9838.683,10106.62
Exp/Cntr=0.3,0.1

Type RM Length L Ch R = 1 ,17203.42,95.961600,95.961600,95.961600
XS GIS Cut Line= 6
866992.740660494 777438.98513417866951.764590549777445.348414981
866923.920686366777452.778470623866875.011416326777473.512237966
866843.632962145777484.151501877866797.310609088777493.359713122
#Sta/Elev= 24
9898.341157.14789916.224156.30849926.384  155.919936.543152.0948 9939.83151.5029
9946.831150.48149957.181150.42839968.648148.81119974.568147.58479978.272 146.051
9989.061142.90159999.888138.086110000.79138.025510010.86 140.69410021.78148.2099
10026.42151.219110032.36154.434410042.91 156.25410053.47 156.57310063.78157.1934
10074.04157.0498 10084.3157.558510094.44157.663910102.19157.5179
#Mann= 3 , 0 , 0
9898.341   0.051       09898.341   0.051       010102.19   0.051       0
#XS Ineff= 2 , 0
       09982.176                       0
Bank Sta=9898.341,10102.19
Exp/Cntr=0.3,0.1

Type RM Length L Ch R = 1 ,17107.46,95.961600,95.961600,95.961600
XS GIS Cut Line= 6
866980.894150858777378.106112721866910.384368108777381.412278516
866887.312480162 777380.23497838866868.480929912777377.592526308
866838.505005299777373.005298295866810.994648196777371.634170996
#Sta/Elev= 25
9888.291154.48029894.191154.50799904.202154.35079914.213153.82989924.224154.0349
9934.235152.57059944.246150.69549954.257148.31529958.878 147.8459964.269147.2939
9974.282145.4424 9981.98141.27619984.317140.00539994.426137.8056    9999137.1308
   10001136.849210004.52136.362310014.64 141.75210018.14144.744310024.75150.2487
10031.32150.743510034.83 151.03710044.85151.948210054.86152.749910058.87152.7642
#Mann= 3 , 0 , 0
9888.291  0.0523       09888.291  0.0523       010058.87  0.0523       0
#XS Ineff= 2 , 0
       0                               0
Bank Sta=9888.291,10058.87
Exp/Cntr=0.3,0.1

Type RM Length L Ch R = 1 ,17011.49,95.961600,95.961600,95.961600
XS GIS Cut Line= 6
867010.052526477 777282.79562419866953.309419162777284.299316401
866882.011538768777282.486037211866880.012608649777282.420627856
866839.511996695777281.002473224866808.359134961777281.394145478
#Sta/Elev= 26
9870.916152.4564 9875.97151.88219885.974152.90259895.977151.34699905.981149.7111
9915.984147.92819925.988146.78879927.679146.52619935.991145.21289945.994144.7454
9955.998143.97019966.001142.75859976.004142.06369986.007138.83879996.011134.1377
    9999134.4145   10001134.599910006.02135.068310016.02138.560510026.03140.6322
10036.03 143.17510041.53 145.33210046.04147.130910056.04 147.95310066.04148.1879
10072.68148.3263
#Mann= 3 , 0 , 0
9870.916    0.12       09870.916    0.12       010072.68    0.12       0
#XS Ineff= 2 , 0
       09954.234                       0
Bank Sta=9870.916,10072.68
Exp/Cntr=0.3,0.1

Type RM Length L Ch R = 1 ,16915.53,95.961600,95.961600,95.961600
XS GIS Cut Line= 6
867018.096601898777157.513112628866974.131984274777163.612127728
866904.367287716  777178.3395538866872.087365082777187.255795758
866870.185609654777187.874929248866794.460636601777209.375809047
#Sta/Elev= 21
9849.823148.59829863.045148.81089873.141142.11549883.237137.63469893.333137.0101
9913.763138.64569944.424 140.0879954.644140.86159964.865141.35869975.229141.5167
9985.604 141.0359990.527136.84739995.978132.447710006.39133.824210016.79136.1841
10027.18 138.13310037.58138.765210047.97141.510910058.37145.678310068.76146.5504
10079.72146.9245
#Mann= 3 , 0 , 0
9849.823    0.04       09849.823    0.04       010079.72    0.04       0
#XS Ineff= 2 , 0
       09969.996                       0
Bank Sta=9849.823,10079.72
Exp/Cntr=0.3,0.1

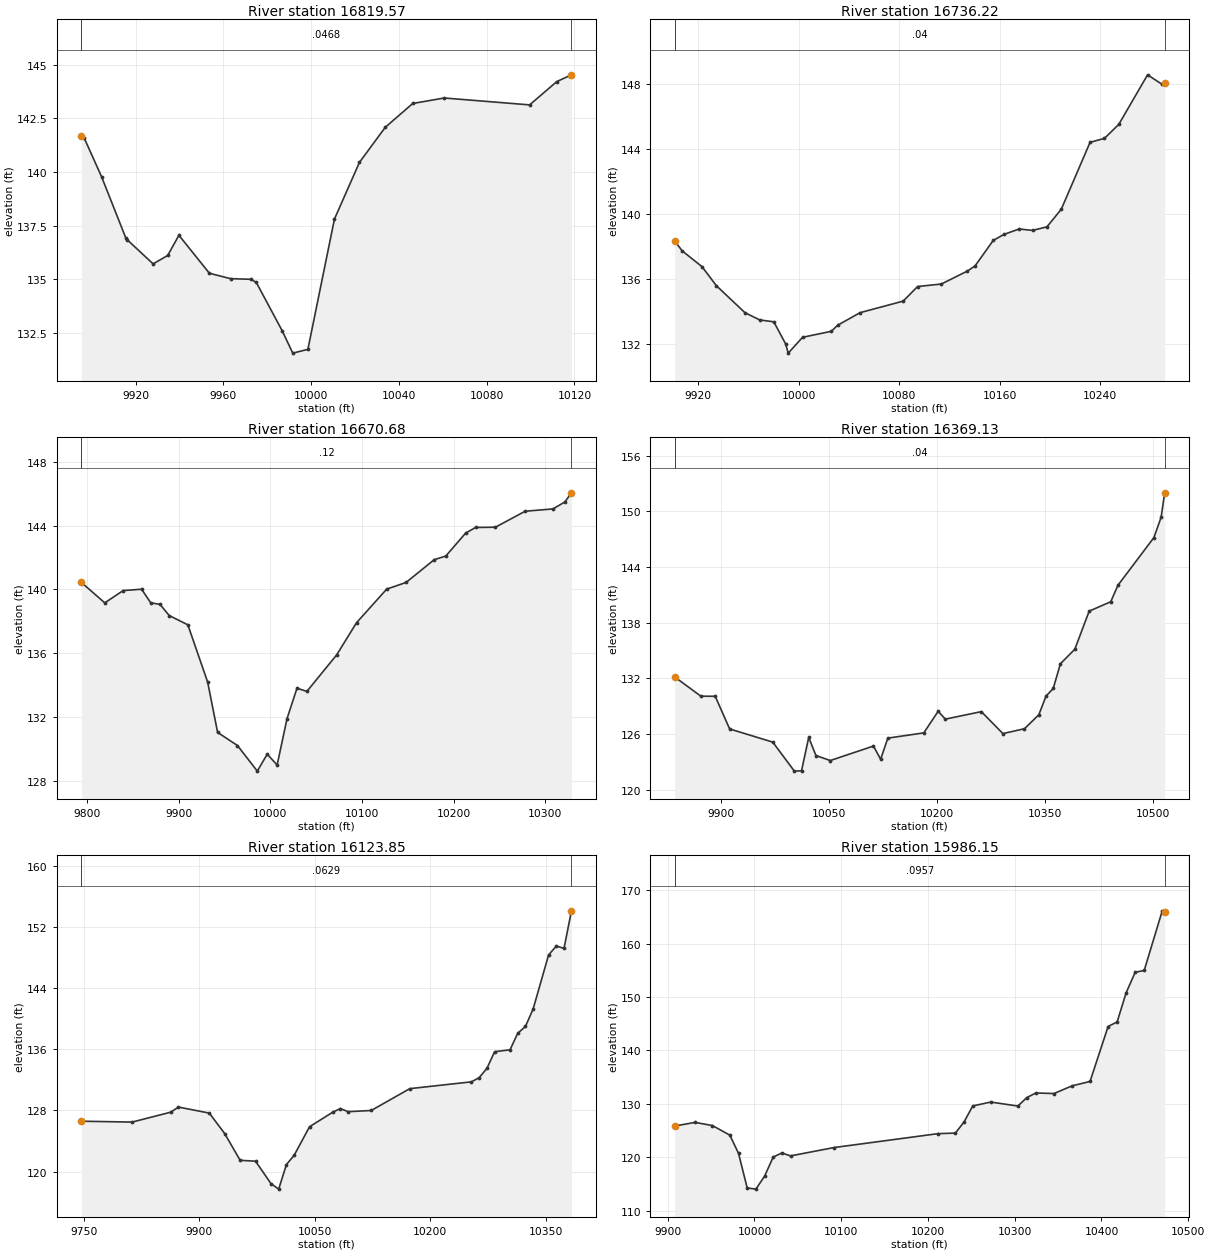
Type RM Length L Ch R = 1 ,16819.57,83.350200,83.350200,83.350200
XS GIS Cut Line= 4
866922.800708664777044.304959295866797.960531831 777121.53550469
866774.614203807777145.568221814866749.251910989777180.419183698
#Sta/Elev= 23
9895.241141.68729896.563141.56899904.414139.7826 9915.57136.90439916.173136.8381
9927.932135.72119934.578136.11269939.691 137.0549953.586135.28419963.209135.0333
9972.594135.00339974.967134.85769986.726132.61479991.601131.56579998.485 131.741
10010.61137.8116   10022140.447910033.76142.079510046.29143.189510060.64143.4449
10099.58143.123710111.95144.208410118.65144.5235
#Mann= 3 , 0 , 0
9895.241  0.0468       09895.241  0.0468       010118.65  0.0468       0
#XS Ineff= 2 , 0
       0 9945.01        10048.37       0
Bank Sta=9895.241,10118.65
Exp/Cntr=0.3,0.1

Type RM Length L Ch R = 1 ,16736.22,65.543300,65.543300,65.543300
XS GIS Cut Line= 2
866873.998108688776982.145721821 866533.09158607777171.135765495
#Sta/Elev= 30
9901.441138.35799907.328137.74759923.163136.77279934.597135.60039957.465133.9318
9969.202133.49229980.332 133.3779989.827132.00219991.766131.4514 10003.2132.4262
10026.07132.793110031.08133.166510048.94133.940210083.24134.651410094.67135.5475
10113.58135.7017 10134.2136.494510140.41136.817310154.82138.380910163.27138.7497
10175.45139.086310186.14138.999210197.58139.219610209.01140.307410231.88144.4175
10243.31144.659810254.74145.523910277.61148.568110289.05147.988810291.23148.0794
#Mann= 3 , 0 , 0
9901.441    0.04       09901.441    0.04       010291.23    0.04       0
#XS Ineff= 2 , 0
       09929.653        10041.91       0
Bank Sta=9901.441,10291.23
Exp/Cntr=0.3,0.1

Type RM Length L Ch R = 1 ,16670.68,301.547300,301.547300,301.547300
XS GIS Cut Line= 3
866950.408641862776950.791402219866838.605911327776939.791185117
 866448.33653536777102.789482777
#Sta/Elev= 30
9793.522140.43599819.053139.1587 9839.15139.92949859.246140.01269869.294139.1581
9879.343139.06739889.391138.36489909.772137.78419931.446134.19049942.283131.0442
9963.958130.22369985.632128.61889996.469  129.6810007.31129.001910018.14131.9119
10028.98133.809810039.82 133.61410072.33135.8996   10094137.911710126.96140.0198
10148.19140.438410178.86141.863710191.54142.091610213.21 143.52810224.05143.8804
10245.72143.896510278.23144.898110308.59145.042210321.58145.4785 10328.8146.0506
#Mann= 3 , 0 , 0
9793.522    0.12       09793.522    0.12       0 10328.8    0.12       0
#XS Ineff= 2 , 0
       09920.768        10058.16       0
Bank Sta=9793.522,10328.8
Exp/Cntr=0.3,0.1

Type RM Length L Ch R = 1 ,16369.13,245.281600,245.281600,245.281600
XS GIS Cut Line= 2
867081.441906981776747.847649411866399.978067073776735.749269121
#Sta/Elev= 30
9835.214132.16969871.661130.09479891.664130.08379911.668126.56949971.677125.1505
10001.68122.028110011.68122.062310021.68125.659610031.69123.705410051.69123.1696
 10111.7124.7263 10121.7123.3042 10131.7125.580110181.71126.144510201.71128.4677
10211.71127.625310261.72128.431610291.73126.068110321.73126.591110341.74128.0971
10351.74130.104610361.74130.922410371.74133.585610391.74135.145910411.75139.2485
10441.75140.260910451.75142.033510501.76147.166910511.76 149.34110516.78151.9834
#Mann= 3 , 0 , 0
9835.214    0.04       09835.214    0.04       010516.78    0.04       0
#XS Ineff= 2 , 0
       09960.775        10143.84       0
Bank Sta=9835.214,10516.78
Exp/Cntr=0.3,0.1

Type RM Length L Ch R = 1 ,16123.85,137.697500,137.697500,137.697500
XS GIS Cut Line= 2
867040.809371147  776560.7353651866405.351522406776607.835126714
#Sta/Elev= 30
9746.548126.58829812.538126.47829862.675127.77129872.702 128.4419912.812127.6544
9932.867 124.9689952.922121.47319972.977121.35689993.032118.421110003.06117.7014
10013.09120.909910023.11122.125410043.17125.863210073.25 127.76610083.28128.2411
10093.31127.837310123.39127.992810173.53130.852310253.74131.743910263.77132.2957
 10273.8133.502410283.83135.683610303.88135.937110313.91138.103510323.94138.9937
10333.96141.297410354.02148.355110364.05149.510910374.07149.217610383.75154.1256
#Mann= 3 , 0 , 0
9746.548  0.0629       09746.548  0.0629       010383.75  0.0629       0
#XS Ineff= 2 , 0
       09909.645         10038.9       0
Bank Sta=9746.548,10383.75
Exp/Cntr=0.3,0.1

Type RM Length L Ch R = 1 ,15986.15,172.091000,172.091000,172.091000
XS GIS Cut Line= 3
866958.608089921776468.613940406866613.767241028776471.491829143
866402.300817882 776532.37789123
#Sta/Elev= 30
9907.972125.83219931.581126.50999951.581125.91499971.582124.12429981.582120.7257
9991.583114.237810001.58114.012410011.58116.419310021.58120.023110031.58 120.789
10041.58120.237810091.59121.798110211.59124.403910231.59124.508210241.59126.5907
10251.59129.592310272.35130.320110303.57129.574910313.98131.159110324.39132.0214
 10345.2131.913710366.01 133.35110386.82134.180710407.64144.471110418.04145.3282
10428.45150.792810438.85154.628210449.26154.971410470.07166.135810472.88165.9319
#Mann= 3 , 0 , 0
9907.972  0.0957       09907.972  0.0957       010472.88  0.0957       0
#XS Ineff= 2 , 0
       09953.019        10106.83       0
Bank Sta=9907.972,10472.88
Exp/Cntr=0.3,0.1