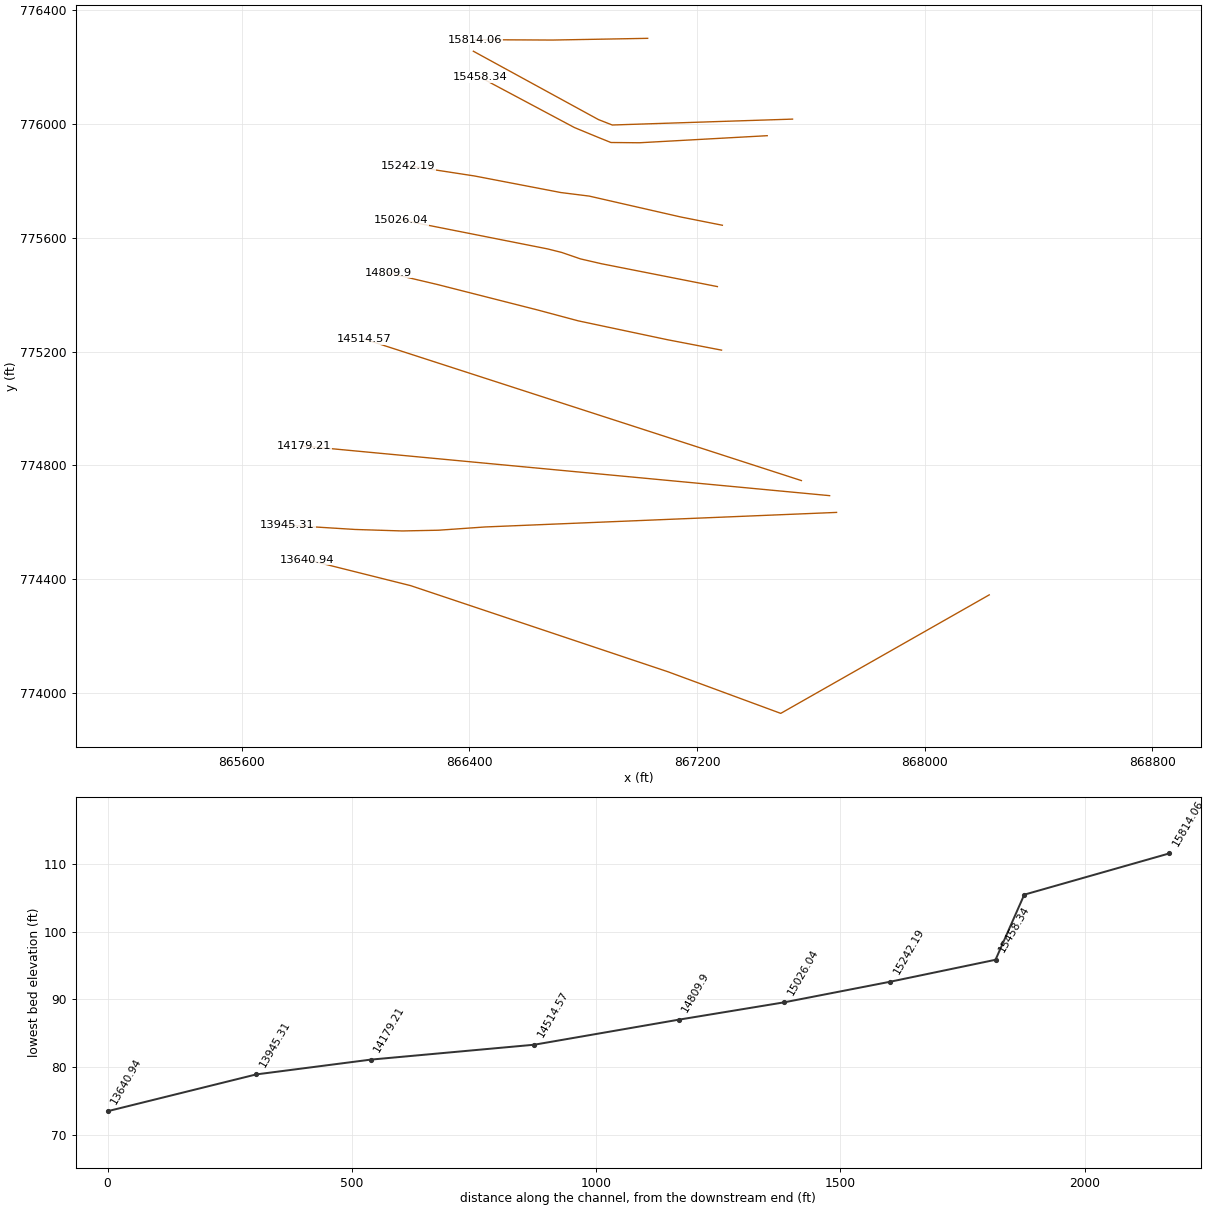
HEC-RAS study 9816_ras.prj: 9816

--- 9816_ras.g01 (geometry) --- (continued)

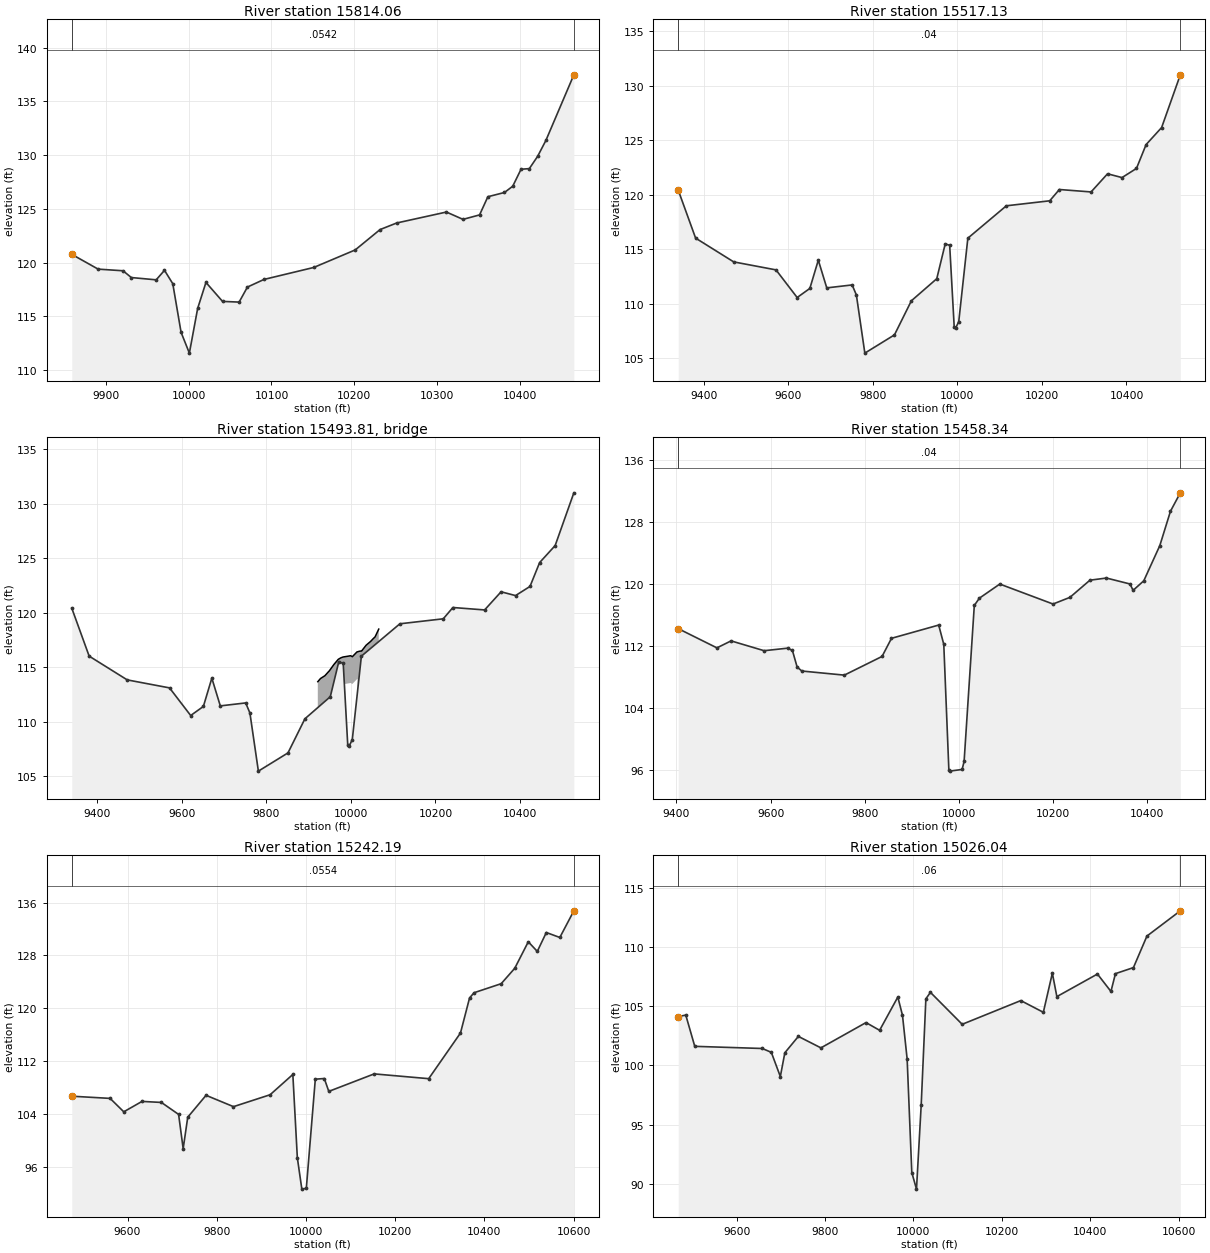
Type RM Length L Ch R = 1 ,15814.06,296.927900,296.927900,296.927900
XS GIS Cut Line= 3
 867026.81793364776301.543831203866691.859080543776295.513114105
866421.300237076 776296.81134538
#Sta/Elev= 30
9859.136 120.7649890.959119.38629920.964119.23419930.965118.6028 9960.97118.3897
9970.972 119.2769980.973118.02859990.975 113.50210000.98111.563710010.98115.7301
10020.98118.148110040.98116.381310060.99116.316610070.99117.715310090.99118.4273
   10151119.542110201.01121.174710231.01123.071410251.01123.683510311.01124.7035
10331.01 124.02110351.01124.436610361.01126.130210381.01126.523510391.01127.1081
10401.01 128.68910411.01128.746710421.01129.888810431.01131.374610464.71137.4826
#Mann= 3 , 0 , 0
9859.136  0.0542       09859.136  0.0542       010464.71  0.0542       0
#XS Ineff= 2 , 0
       09934.977        10084.78       0
Bank Sta=9859.136,10464.71
Exp/Cntr=0.3,0.1

Type RM Length L Ch R = 1 ,15517.13,58.795800,58.795800,58.795800
XS GIS Cut Line= 4
 867536.07467372776017.579751341866902.332687145775996.850123255
866853.589924698 776015.96054554 866414.00894315776256.193198895
#Sta/Elev= 30
9339.944120.4125 9381.04116.01389471.089113.83379571.142113.10069621.169110.5676
9651.185111.39939671.196113.99179691.206111.45049751.238111.72119761.244110.7996
9781.254105.46859851.292 107.1419891.313110.26759951.345112.29059971.356115.4875
9981.901 115.3519992.642107.83659996.352107.792210003.38108.366710024.87116.0079
10115.94118.9771 10218.5119.4346 10241.3120.470310316.31120.247510355.25121.9107
10389.44121.563610423.63122.402510446.42124.590410483.13126.150510527.32130.9849
#Mann= 3 , 0 , 0
9339.944    0.04       09339.944    0.04       010527.32    0.04       0
#XS Ineff= 2 , 0
       09976.324        10025.65       0
Bank Sta=9339.944,10527.32
Exp/Cntr=0.3,0.1

Type RM Length L Ch R = 3 ,15493.81,,,
BEGIN DESCRIPTION:
END DESCRIPTION:
Bridge Culvert--1,0,-1,-1, 0
Deck Dist Width WeirC Skew NumUp NumDn MinLoCord MaxHiCord MaxSubmerge Is_Ogee
14.397900,30.000000,2.6,0, 26, 26, , , 0.95, 0, 0,0,,
 9921.81 9928.16 9938.68 9946.04 9949.20 9959.73 9969.79 9970.27 9975.90 9981.33
 9985.76 9985.76 9992.38 9999.3510003.4410014.4910015.7610015.7610020.2210023.45
10025.3510035.9910046.6310052.7410057.2710065.92
  113.67  113.96  114.22  114.54  114.67  115.24  115.70  115.72  115.85  115.93
  115.96  115.96  116.00  116.05  115.96  116.40  116.41  116.41  116.46  116.48
  116.48  117.01  117.36  117.61  117.78  118.49
 -886.33 -886.04 -885.78 -885.46 -885.33 -884.76 -884.30 -884.28 -884.15 -884.07
 -884.04  113.46  113.50  113.55  113.46  113.90  113.91 -883.59 -883.54 -883.52
 -883.52 -882.99 -882.64 -882.39 -882.22 -881.51
 9921.81 9928.16 9938.68 9946.04 9949.20 9959.73 9969.79 9970.27 9975.90 9981.33
 9984.03 9984.03 9992.38 9999.3510003.4410014.0310014.0310014.4910020.2210023.45
10025.3510035.9910046.6310052.7410057.2710065.92
  113.67  113.96  114.22  114.54  114.67  115.24  115.70  115.72  115.85  115.93
  115.94  115.94  116.00  116.05  115.96  116.38  116.38  116.40  116.46  116.48
  116.48  117.01  117.36  117.61  117.78  118.49
 -886.33 -886.04 -885.78 -885.46 -885.33 -884.76 -884.30 -884.28 -884.15 -884.07
 -884.06  113.44  113.50  113.55  113.46  113.88 -883.62 -883.60 -883.54 -883.52
 -883.52 -882.99 -882.64 -882.39 -882.22 -881.51
BR Coef=-1 , 0 , 0 ,, 0 ,,,0.8,0,1,0,
WSPro=,,,, 1 ,,,, 0 ,,,, 0 ,,,,-1 ,-1 ,-1 , 0 , 0 , 0 , 0 , 0
BC Design=,, 0 ,, 0 ,,,,,,

Type RM Length L Ch R = 1 ,15458.34,216.146800,216.146800,216.146800
XS GIS Cut Line= 6
867447.007002622775959.294060247866997.835872454 775934.43027119
866897.586190026775935.327982175866851.332103405775953.968302793
866769.218900271775987.923866398866436.586740476776165.238749352
#Sta/Elev= 30
9404.006114.22319486.139111.74419516.185112.64429586.292111.37829636.368111.7074
9646.384111.40929656.399109.26939666.414108.75859756.552 108.2299836.674110.6395
9856.701112.97629956.907114.68379967.688112.1993 9978.4796.018199979.99495.85279
10006.6196.0677710010.8597.1075110032.49117.214810043.31118.151810086.59119.9708
10199.61117.396610235.44118.254710277.95120.469610312.93120.747410362.99119.9809
 10369.6119.159610392.26120.392810426.26124.925610448.92129.363110469.79131.7331
#Mann= 3 , 0 , 0
9404.006    0.04       09404.006    0.04       010469.79    0.04       0
#XS Ineff= 2 , 0
       09968.853         10029.2       0
Bank Sta=9404.006,10469.79
Exp/Cntr=0.3,0.1

Type RM Length L Ch R = 1 ,15242.19,216.146700,216.146700,216.146700
XS GIS Cut Line= 6
867289.399701245775644.437480272867142.624187464775673.583796338
866821.107265702775746.967272887866721.455593009775759.422765537
866418.202358782775817.647885951866183.895708664775853.708542728
#Sta/Elev= 30
9475.023106.67459561.015106.3414 9591.63104.31049632.491105.88519675.975105.7302
9714.548103.91889724.80598.735029735.062103.49279776.091  106.819837.634 105.092
9919.691106.89299970.701109.96599980.78697.354189990.87292.6026310000.9492.73655
10021.09 109.25310041.24109.351210051.32107.4028 10153.1 110.052 10275.3109.3285
10346.58116.241810366.92121.550410377.06122.343810437.85 123.71110468.25126.0439
10498.61130.056710518.81128.598410539.02 131.46110569.33130.709410600.76134.7447
#Mann= 3 , 0 , 0
9475.023  0.0554       09475.023  0.0554       010600.76  0.0554       0
#XS Ineff= 2 , 0
       09955.088        10045.26       0
Bank Sta=9475.023,10600.76
Exp/Cntr=0.3,0.1

Type RM Length L Ch R = 1 ,15026.04,216.146800,216.146800,216.146800
XS GIS Cut Line= 6
867271.797565916775428.802450259866864.116033351775509.181167865
866790.940056991775526.030132423866724.576923015775548.818608157
866674.833829956775561.285103249866160.806771932775663.029002923
#Sta/Elev= 30
9467.867104.12269484.943104.24419505.275101.61099658.095101.42939678.496101.1046
9698.89799.063599709.098101.0694  9739.7102.44889790.702101.48219892.763103.6139
9923.548102.9632 9964.76105.76889975.301104.22589985.841100.54039996.38190.96986
   10007 89.570810017.6196.6393710028.22105.618210038.54106.162810110.39103.4686
10243.01 105.46910294.01104.481710314.42107.781310324.62105.804110416.43 107.707
   10447106.238710457.18 107.741 10497.9108.250410528.44110.909710603.96113.0375
#Mann= 3 , 0 , 0
9467.867    0.06       09467.867    0.06       010603.96    0.06       0
#XS Ineff= 2 , 0
       09965.808        10047.79       0
Bank Sta=9467.867,10603.96
Exp/Cntr=0.3,0.1

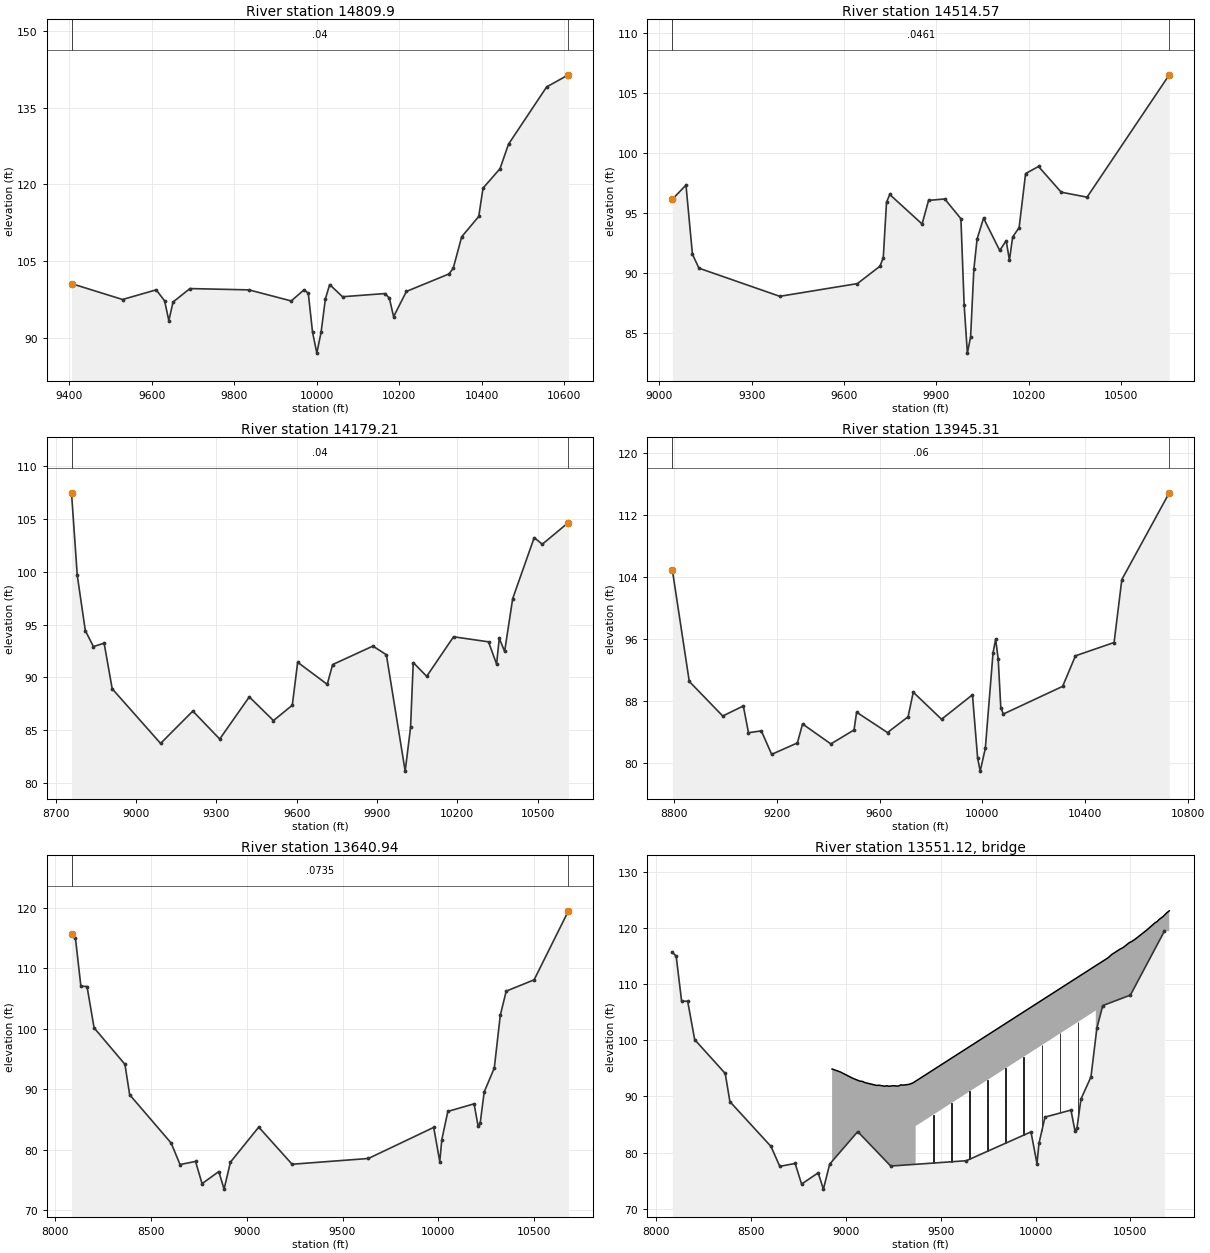
Type RM Length L Ch R = 1 , 14809.9,295.326800,295.326800,295.326800
XS GIS Cut Line= 6
867286.451030444775205.401124046 867095.52240543775242.165654634
866782.439881319775308.427808895866641.188716072775346.231559578
 866288.08470098 775435.97784146866113.605334316775477.133066862
#Sta/Elev= 30
9405.584100.59939529.26697.492679610.77699.383199631.21997.23033 9641.4493.36168
9651.66296.998239692.54899.631879835.64999.373899938.06197.209359969.06499.39042
9979.39898.708859989.73391.0813910000.0887.0046210010.4591.1164210020.82 97.6079
 10031.2100.412310062.3198.0346510165.5198.6567910175.8397.7548810186.1594.12999
 10217.199.0700110320.28102.4883 10330.6 103.59710351.23109.769110392.51113.7378
10402.82119.262710444.04123.082610464.59127.868410557.06139.073110609.86141.4324
#Mann= 3 , 0 , 0
9405.584    0.04       09405.584    0.04       010609.86    0.04       0
#XS Ineff= 2 , 0
       09969.613         10043.6       0
Bank Sta=9405.584,10609.86
Exp/Cntr=0.3,0.1

Type RM Length L Ch R = 1 ,14514.57,335.361100,335.361100,335.361100
XS GIS Cut Line= 2
 867567.18442131 774746.80572682866030.873296781775244.025030056
#Sta/Elev= 30
9041.96496.140219086.30297.330249107.32491.564679128.34590.397829391.112 88.0496
9643.369 89.10999716.94490.566149727.45591.283039737.96595.893839748.47696.54266
9853.58394.081529874.60496.051229927.15896.170819979.71194.523019990.22287.34973
10000.7383.3104210011.2484.6667710021.7590.2903710032.2692.8214710053.2994.56992
10105.8491.8722710126.8692.6913310137.3791.0679510147.8892.99948 10168.993.78605
10189.9298.2910110231.9798.8799610305.5496.7356510389.6396.3210510656.73106.5252
#Mann= 3 , 0 , 0
9041.964  0.0461       09041.964  0.0461       010656.73  0.0461       0
#XS Ineff= 2 , 0
       09966.907        10063.49       0
Bank Sta=9041.964,10656.73
Exp/Cntr=0.3,0.1

Type RM Length L Ch R = 1 ,14179.21,233.899200,233.899200,233.899200
XS GIS Cut Line= 2
867666.371631421774693.829071513865817.591024941774868.126908303
#Sta/Elev= 30
8758.393107.50258779.859 99.67998809.99294.432868840.12592.919988880.30393.23592
8910.436 88.91439091.23483.731099211.76686.800419312.20984.147019422.69788.14476
9513.09685.898189583.40787.355149603.49591.428629713.983 89.33439734.07291.20875
9884.73792.966459934.95992.1409710005.2781.1025510025.3685.26151 10035.491.40057
10085.6290.0954510186.0793.8489410316.6493.3668710346.7891.2600110356.8293.69532
10376.9192.4611110407.0497.46893 10487.4103.253610517.53102.624410615.37104.6868
#Mann= 3 , 0 , 0
8758.393    0.04       08758.393    0.04       010615.37    0.04       0
#XS Ineff= 2 , 0
       09881.018        10064.51       0
Bank Sta=8758.393,10615.37
Exp/Cntr=0.3,0.1

Type RM Length L Ch R = 1 ,13945.31,304.367500,304.367500,304.367500
XS GIS Cut Line= 6
867690.817790607774634.920470363866454.814303255774583.758275556
866291.746862999774572.330954764866163.808533701774569.726054314
865998.813393075774574.948519942 865760.96304891774589.748228161
#Sta/Elev= 30
8794.384104.88628860.25990.488968990.37286.028689070.44287.324939090.45983.87509
9140.50384.112249180.53881.085369280.62582.557289300.64285.005379410.738 82.4299
9500.81684.230589510.82586.51798 9630.9383.89479    971185.931719731.01789.10095
9841.113 85.6126 9961.2188.765499981.22280.607389991.22878.9219410011.2481.85628
10041.2994.2001610051.3195.9221510061.3393.3551310071.3687.0910410081.38 86.2867
10311.6989.8499310361.71 93.793710511.8295.5065510541.87 103.62210726.27114.8063
#Mann= 3 , 0 , 0
8794.384    0.06       08794.384    0.06       010726.27    0.06       0
#XS Ineff= 2 , 0
       09906.165        10055.58       0
Bank Sta=8794.384,10726.27
Exp/Cntr=0.3,0.1

Type RM Length L Ch R = 1 ,13640.94,179.857500,179.857500,179.857500
XS GIS Cut Line= 5
868227.532023153774345.022158496867494.581084341773928.426358427
867098.046744013774074.729242945866193.498083929 774377.46177932
  865829.7101755774468.506640438
#Sta/Elev= 30
8084.795 115.7028105.077115.03338133.717107.01688165.788106.96748202.731100.1369
8363.76594.105858388.39789.084928605.31681.085818651.326 77.54698732.428 78.0606
 8766.3574.391348853.85176.386488881.37473.483268914.563 77.94459062.41583.73138
9236.52877.594439634.95878.548729975.90883.6869810007.5478.0342610018.0981.64141
10049.72 86.324710186.81 87.5792 10207.983.8578310218.45 84.370810239.5489.54739
10292.26 93.494710323.46102.200410354.39106.1993 10500.2108.0741 10679.4119.4736
#Mann= 3 , 0 , 0
8084.795  0.0735       08084.795  0.0735       0 10679.4  0.0735       0
#XS Ineff= 2 , 0
       09437.289        10067.04       0
Bank Sta=8084.795,10679.4
Exp/Cntr=0.3,0.1

Type RM Length L Ch R = 3 ,13551.12,,,
BEGIN DESCRIPTION:
END DESCRIPTION:
Bridge Culvert--1,0,-1,-1, 0
Deck Dist Width WeirC Skew NumUp NumDn MinLoCord MaxHiCord MaxSubmerge Is_Ogee
43.928750,92.000000,2.6,0, 36, 36, , , 0.95, 0, 0,0,,
 8927.24 8971.55 9035.32 9073.60 9088.45 9099.08 9162.21 9173.47 9205.36 9215.98
 9226.61 9250.83 9269.12 9279.75 9290.38 9301.00 9332.89 9353.53 9367.77 9367.77
10317.7710317.7710383.0610401.4810443.1010463.9110495.1310505.5310526.3410588.77
10630.3910640.8010651.2010672.0110692.8210705.04
   94.90   94.36   93.26   92.74   92.68   92.49   91.97   92.01   91.83   91.92
   91.82   91.93   91.85   91.90   92.08   92.02   92.16   92.42   92.73   92.73
  113.33  113.33  114.74  115.31  116.22  116.60  117.45  117.60  118.07  119.74
  120.98  121.17  121.55  122.07  122.77  123.10
 -905.10 -905.64 -906.74 -907.26 -907.32 -907.51 -908.03 -907.99 -908.17 -908.08
 -908.18 -908.07 -908.15 -908.10 -907.92 -907.98 -907.84 -907.58 -907.27   84.73
  105.33 -886.67 -885.26 -884.69 -883.78 -883.40 -882.55 -882.40 -881.93 -880.26
 -879.02 -878.83 -878.45 -877.93 -877.23 -876.90
 8927.24 8971.55 9035.32 9073.60 9088.45 9099.08 9162.21 9173.47 9205.36 9215.98
 9226.61 9250.83 9269.12 9279.75 9290.38 9301.00 9332.89 9353.53 9418.78 9418.78
10368.7810368.7810383.0610401.4810443.1010453.5110495.1310505.5310526.3410588.77
10630.3910640.8010651.2010672.0110692.8210705.04
   94.90   94.36   93.26   92.74   92.68   92.49   91.97   92.01   91.83   91.92
   91.82   91.93   91.85   91.90   92.08   92.02   92.16   92.42   93.84   93.84
  114.43  114.43  114.74  115.31  116.22  116.37  117.45  117.60  118.07  119.74
  120.98  121.17  121.55  122.07  122.77  123.10
 -905.10 -905.64 -906.74 -907.26 -907.32 -907.51 -908.03 -907.99 -908.17 -908.08
 -908.18 -908.07 -908.15 -908.10 -907.92 -907.98 -907.84 -907.58 -906.16   85.84
  106.43 -885.57 -885.26 -884.69 -883.78 -883.63 -882.55 -882.40 -881.93 -880.26
 -879.02 -878.83 -878.45 -877.93 -877.23 -876.90
Pier Skew, UpSta & Num, DnSta & Num=  ,9461.17, 2 ,9512.18, 2 , 0 , 0 , 0 ,,
    4.00    4.00
 -905.25   94.75
    4.00    4.00
 -904.14   95.86
Pier Skew, UpSta & Num, DnSta & Num=  ,9556.57, 2 ,9607.58, 2 , 0 , 0 , 0 ,,
    4.00    4.00
 -903.18   96.82
    4.00    4.00
 -902.07   97.93
Pier Skew, UpSta & Num, DnSta & Num=  ,9651.97, 2 ,9702.98, 2 , 0 , 0 , 0 ,,
    4.00    4.00
 -901.11   98.89
    4.00    4.00
 -900.00  100.00
Pier Skew, UpSta & Num, DnSta & Num=  ,9747.37, 2 ,9798.38, 2 , 0 , 0 , 0 ,,
    4.00    4.00
 -899.04  100.96
    4.00    4.00
 -897.93  102.07
Pier Skew, UpSta & Num, DnSta & Num=  ,9842.77, 2 ,9893.78, 2 , 0 , 0 , 0 ,,
    4.00    4.00
 -896.97  103.03
    4.00    4.00
 -895.87  104.13
Pier Skew, UpSta & Num, DnSta & Num=  ,9938.17, 2 ,9989.18, 2 , 0 , 0 , 0 ,,
    4.00    4.00
 -894.90  105.10
    4.00    4.00
 -893.80  106.20
Pier Skew, UpSta & Num, DnSta & Num=  ,10033.57, 2 ,10084.58, 2 , 0 , 0 , 0 ,,
    4.00    4.00
 -892.84  107.16
    4.00    4.00
 -891.73  108.27
Pier Skew, UpSta & Num, DnSta & Num=  ,10128.97, 2 ,10179.98, 2 , 0 , 0 , 0 ,,
    4.00    4.00
 -890.77  109.23
    4.00    4.00
 -889.66  110.34
Pier Skew, UpSta & Num, DnSta & Num=  ,10224.37, 2 ,10275.38, 2 , 0 , 0 , 0 ,,
    4.00    4.00
 -888.70  111.30
    4.00    4.00
 -887.59  112.41
BR Coef=-1 , 0 , 0 ,, 0 ,,,0.8,0,1,0,
WSPro=,,,, 1 ,,,, 0 ,,,, 0 ,,,,-1 ,-1 ,-1 , 0 , 0 , 0 , 0 , 0
BC Design=,, 0 ,, 0 ,,,,,,