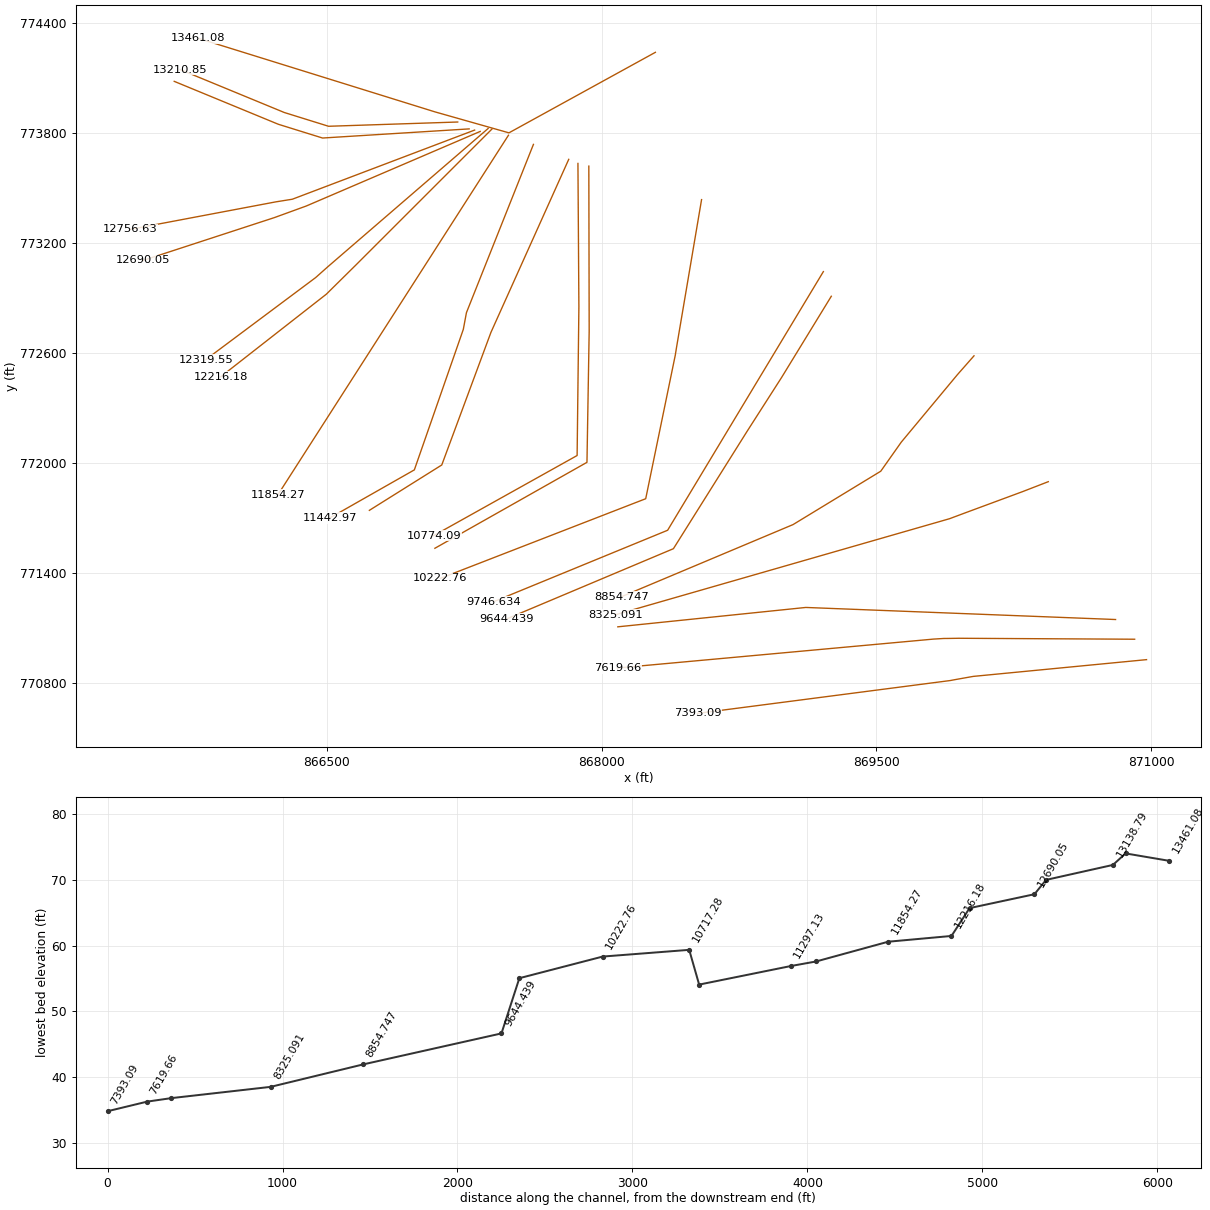
HEC-RAS study 9816_ras.prj: 9816

--- 9816_ras.g01 (geometry) --- (continued)

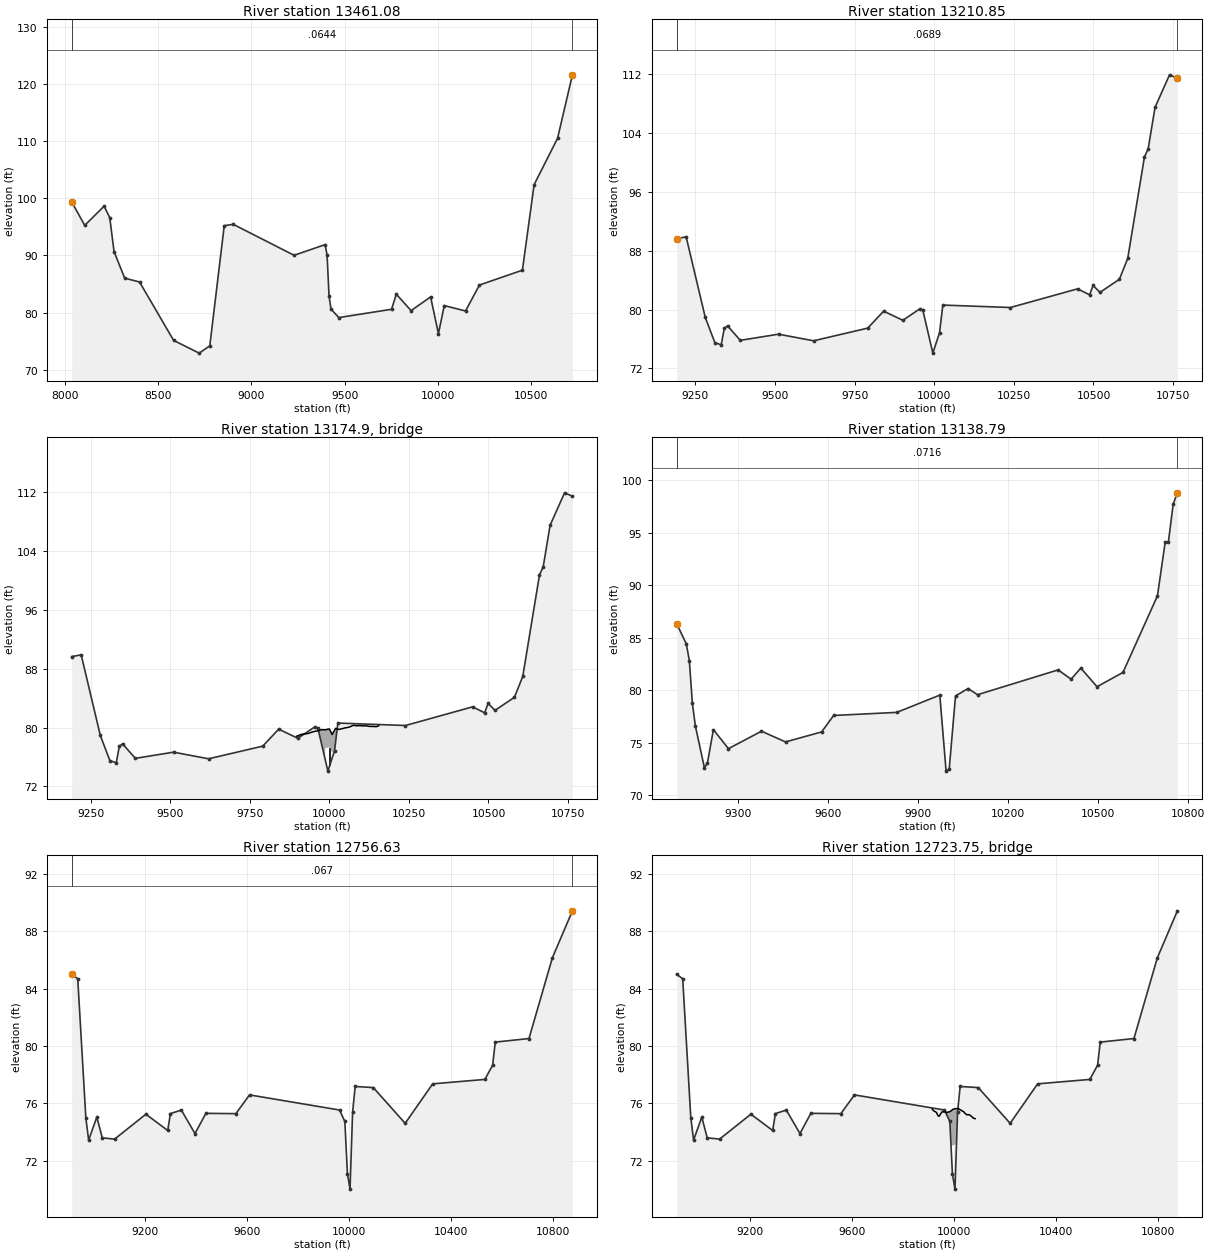
Type RM Length L Ch R = 1 ,13461.08,250.235700,250.235700,250.235700
XS GIS Cut Line= 4
868293.894774673 774238.62968332867494.479867154773799.613724399
867090.625016137773913.908273867865799.042007853 774314.86810095
#Sta/Elev= 30
8036.92499.362098106.788 95.2528 8210.6698.61266 8241.0296.588638263.838 90.6876
8320.88186.040488400.74285.358728583.28275.156138720.18772.93519 8777.2374.21143
8854.66795.201028902.72695.440439229.01890.029549395.502 91.89319405.97390.04998
9416.444 82.92089426.91580.626119468.79879.146729751.50980.595859777.09983.23135
9856.21780.360579960.92582.7587310002.8176.3513510034.2281.2429910148.1280.29895
10222.6984.8328910453.0587.4264510515.88 102.37810641.53110.470210721.06121.5573
#Mann= 3 , 0 , 0
8036.924  0.0644       08036.924  0.0644       010721.06  0.0644       0
#XS Ineff= 2 , 0
       09487.571        10062.57       0
Bank Sta=8036.924,10721.06
Exp/Cntr=0.3,0.1

Type RM Length L Ch R = 1 ,13210.85,72.057200,72.057200,72.057200
XS GIS Cut Line= 4
867214.772483775773858.651122927866509.799149983773835.401660845
866268.208445813   773910.463084865700.179849434774144.369861744
#Sta/Elev= 30
9190.91489.656019220.70289.890439280.73578.930589310.75175.507289330.76275.19705
9340.76877.487449350.77377.778889390.79575.80856 9510.8676.64668 9620.92 75.7468
9791.01277.47005 9841.0479.782759901.296 78.53399953.65480.065519964.12579.90518
 9995.5474.0678210016.4876.8419810026.95 80.608210239.2480.2768410450.0682.81604
10487.9882.0040410498.7983.2832610520.4282.3353510581.3784.1120910607.6486.95538
10660.16100.766210671.83101.871510693.46107.521210738.95111.941210763.56111.4792
#Mann= 3 , 0 , 0
9190.914  0.0689       09190.914  0.0689       010763.56  0.0689       0
#XS Ineff= 2 , 0
       09444.023        10284.41       0
Bank Sta=9190.914,10763.56
Exp/Cntr=0.3,0.1

Type RM Length L Ch R = 3 , 13174.9,,,
BEGIN DESCRIPTION:
END DESCRIPTION:
Bridge Culvert--1,0,-1,-1, 0
Deck Dist Width WeirC Skew NumUp NumDn MinLoCord MaxHiCord MaxSubmerge Is_Ogee
14.528600,43.000000,2.6,0, 41, 41, , , 0.95, 0, 0,0,,
 9897.65 9902.33 9912.86 9913.43 9923.40 9933.93 9944.46 9945.26 9955.00 9965.53
 9967.95 9975.19 9976.34 9986.97 9986.97 9987.24 9998.1310000.3910009.0310015.97
10015.9710019.9210025.5910030.8110041.7110050.7910052.6010063.5010068.0510074.16
10078.4010084.6610095.1610105.6610111.2310116.1610126.6610137.1510144.0610147.65
10155.46
   78.82   78.89   79.08   79.08   79.13   79.20   79.36   79.38   79.48   79.57
   79.59   79.71   79.71   79.69   79.69   79.69   79.80   79.79   79.06   79.59
   79.59   79.89   79.82   79.74   79.86   79.97   79.96   80.08   80.15   80.29
   80.30   80.24   80.27   80.22   80.23   80.24   80.15   80.15   80.13   80.12
   80.25
 -921.18 -921.11 -920.92 -920.92 -920.87 -920.80 -920.64 -920.62 -920.52 -920.43
 -920.41 -920.29 -920.29 -920.31   77.19   77.19   77.30   77.29   76.56   77.09
 -920.41 -920.11 -920.18 -920.26 -920.14 -920.03 -920.04 -919.92 -919.85 -919.71
 -919.70 -919.76 -919.73 -919.78 -919.77 -919.76 -919.85 -919.85 -919.87 -919.88
 -919.75
 9897.65 9902.33 9912.86 9913.43 9923.40 9933.93 9944.46 9945.26 9955.00 9965.53
 9967.95 9975.19 9976.34 9983.97 9983.97 9987.24 9998.1310000.3910009.0310012.97
10012.9710019.9210025.5910030.8110041.7110050.7910052.6010063.5010068.0510074.16
10078.4010084.6610095.1610105.6610111.2310116.1610126.6610137.1510144.0610147.65
10155.46
   78.82   78.89   79.08   79.08   79.13   79.20   79.36   79.38   79.48   79.57
   79.59   79.71   79.71   79.70   79.70   79.69   79.80   79.79   79.06   79.36
   79.36   79.89   79.82   79.74   79.86   79.97   79.96   80.08   80.15   80.29
   80.30   80.24   80.27   80.22   80.23   80.24   80.15   80.15   80.13   80.12
   80.25
 -921.18 -921.11 -920.92 -920.92 -920.87 -920.80 -920.64 -920.62 -920.52 -920.43
 -920.41 -920.29 -920.29 -920.30   77.20   77.19   77.30   77.29   76.56   76.86
 -920.64 -920.11 -920.18 -920.26 -920.14 -920.03 -920.04 -919.92 -919.85 -919.71
 -919.70 -919.76 -919.73 -919.78 -919.77 -919.76 -919.85 -919.85 -919.87 -919.88
 -919.75
Pier Skew, UpSta & Num, DnSta & Num=  ,10001.47, 2 ,9998.47, 2 , 0 , 0 , 0 ,,
    2.00    2.00
 -920.30   79.70
    2.00    2.00
 -920.20   79.80
BR Coef=-1 , 0 , 0 ,, 0 ,,,0.8,0,1,0,
WSPro=,,,, 1 ,,,, 0 ,,,, 0 ,,,,-1 ,-1 ,-1 , 0 , 0 , 0 , 0 , 0
BC Design=,, 0 ,, 0 ,,,,,,

Type RM Length L Ch R = 1 ,13138.79,382.160200,382.160200,382.160200
XS GIS Cut Line= 4
 867277.19233664773821.133210128866477.007022983773771.324354286
866235.416114657773846.385977491865667.387068145774080.293282642
#Sta/Elev= 30
9094.94486.355269127.19884.412359137.21882.830149147.23778.772559157.25676.61613
9187.31472.646639197.33473.053679217.37276.260769267.46974.452619377.68276.11265
9457.83775.093329578.06976.045029618.147  77.6119828.55377.90426 9972.0879.54854
9993.02372.3131210003.4972.5295510024.4479.4726910066.3280.1740410097.7479.58672
 10366.481.9474710409.6681.0646210442.1182.1217710496.1880.34576 10582.781.71078
10697.5488.9999610723.2994.09863 10734.194.1421310750.0697.7321510763.9698.80352
#Mann= 3 , 0 , 0
9094.944  0.0716       09094.944  0.0716       010763.96  0.0716       0
#XS Ineff= 2 , 0
       09417.912        10326.48       0
Bank Sta=9094.944,10763.96
Exp/Cntr=0.3,0.1

Type RM Length L Ch R = 1 ,12756.63,66.582100,66.582100,66.582100
XS GIS Cut Line= 4
867307.123847019773814.654630689866312.055154409 773437.66539686
866222.086023216773423.309492965865427.670478473773273.314103958
#Sta/Elev= 30
 8913.2684.988418936.91884.682698968.73774.990648979.69373.448489011.77375.04875
9033.16173.603479081.64173.518669204.25875.251269289.80774.118389300.50175.29535
9343.27575.537819396.74373.903219439.51875.311139557.148 75.28979610.61676.59508
9963.50575.542489984.49274.746919994.61871.1110110004.74  70.03510014.8775.38212
   1002577.1817110096.0277.1046310221.0474.6166710328.84 77.364310533.6277.67217
10564.1578.6673210574.3280.2700810706.6280.5195910798.2186.1304610876.9189.40968
#Mann= 3 , 0 , 0
 8913.26   0.067       0 8913.26   0.067       010876.91   0.067       0
#XS Ineff= 2 , 0
       09309.096        10038.68       0
Bank Sta=8913.26,10876.91
Exp/Cntr=0.3,0.1

Type RM Length L Ch R = 3 ,12723.75,,,
BEGIN DESCRIPTION:
END DESCRIPTION:
Bridge Culvert--1,0,-1,-1, 0
Deck Dist Width WeirC Skew NumUp NumDn MinLoCord MaxHiCord MaxSubmerge Is_Ogee
11.291050,44.000000,2.6,0, 29, 29, , , 0.95, 0, 0,0,,
 9915.25 9920.83 9931.65 9938.59 9942.47 9953.30 9964.12 9964.74 9974.94 9982.14
 9982.14 9985.76 9990.90 9996.5910007.4110012.1410012.1410017.0610018.2310029.05
10039.8710043.2110050.7010053.6510061.1910071.5610076.3410081.9310083.74
   75.61   75.49   75.38   75.14   75.10   75.41   75.41   75.41   75.38   75.42
   75.42   75.44   75.51   75.59   75.64   75.64   75.64   75.64   75.64   75.52
   75.41   75.33   75.21   75.22   75.21   75.07   74.98   74.95   74.94
 -924.39 -924.51 -924.62 -924.86 -924.90 -924.59 -924.59 -924.59 -924.62 -924.58
   72.92   72.94   73.01   73.09   73.14   73.14 -924.36 -924.36 -924.36 -924.48
 -924.59 -924.67 -924.79 -924.78 -924.79 -924.93 -925.02 -925.05 -925.06
 9915.25 9920.83 9931.65 9938.59 9942.47 9953.30 9964.12 9964.74 9973.97 9973.97
 9974.94 9985.76 9990.90 9996.5910003.9710003.9710007.4110017.0610018.2310029.05
10039.8710043.2110050.7010053.6510061.1910071.5610076.3410081.9310083.74
   75.61   75.49   75.38   75.14   75.10   75.41   75.41   75.41   75.38   75.38
   75.38   75.44   75.51   75.59   75.63   75.63   75.64   75.64   75.64   75.52
   75.41   75.33   75.21   75.22   75.21   75.07   74.98   74.95   74.94
 -924.39 -924.51 -924.62 -924.86 -924.90 -924.59 -924.59 -924.59 -924.62   72.88
   72.88   72.94   73.01   73.09   73.13 -924.37 -924.36 -924.36 -924.36 -924.48
 -924.59 -924.67 -924.79 -924.78 -924.79 -924.93 -925.02 -925.05 -925.06
BR Coef=-1 , 0 , 0 ,, 0 ,,,0.8,0,1,0,
WSPro=,,,, 1 ,,,, 0 ,,,, 0 ,,,,-1 ,-1 ,-1 , 0 , 0 , 0 , 0 , 0
BC Design=,, 0 ,, 0 ,,,,,,

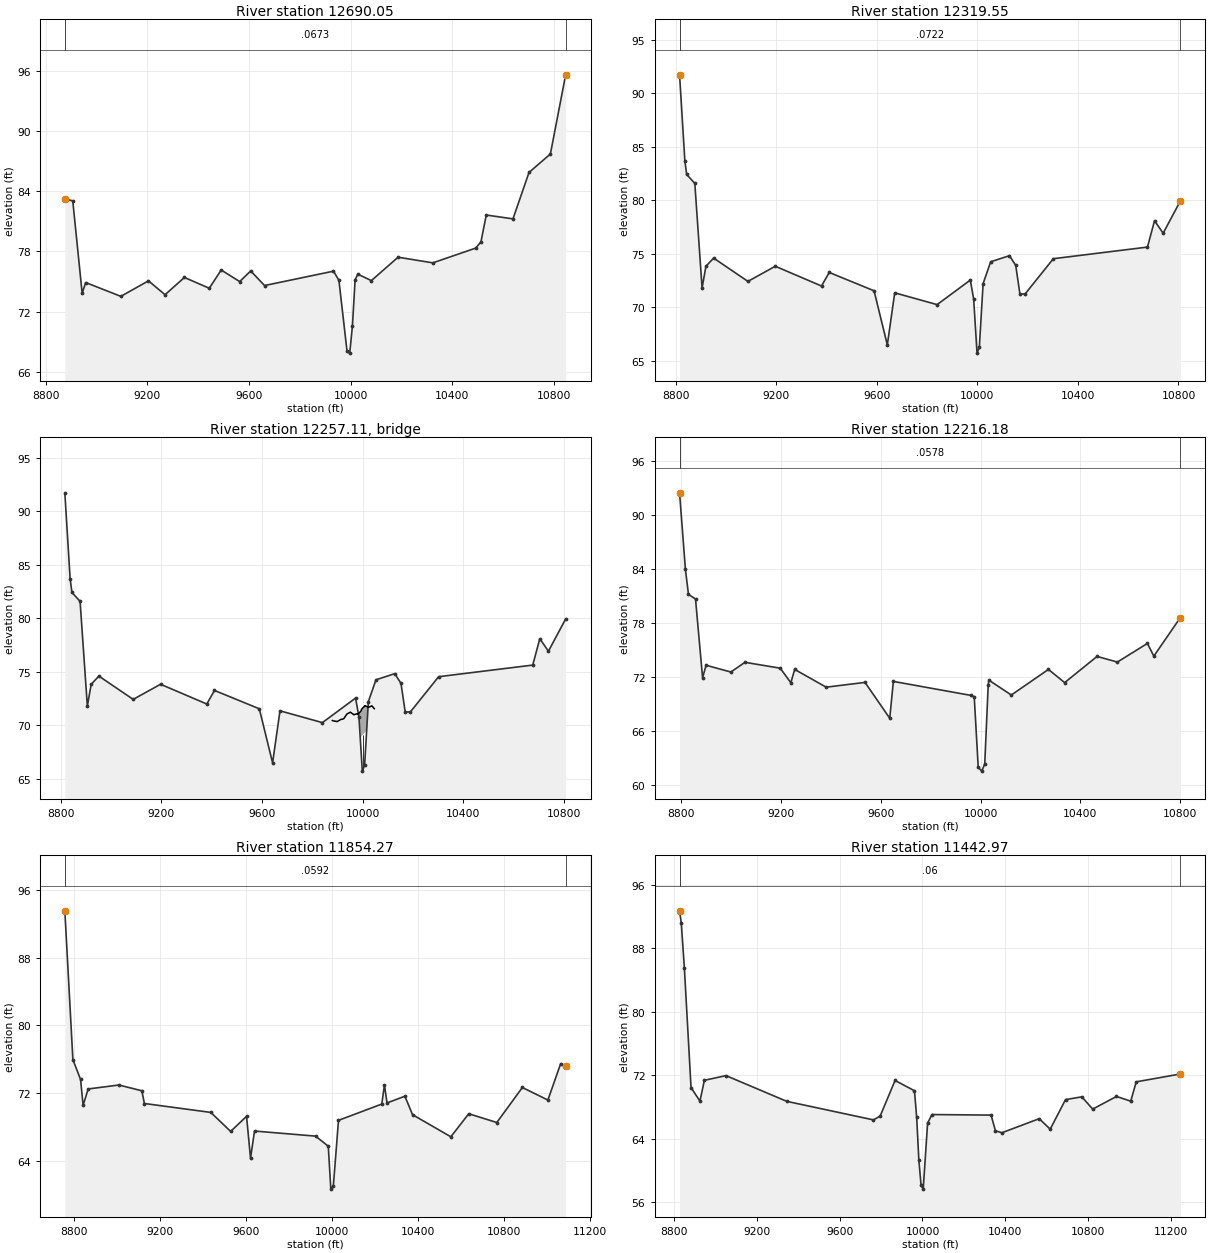
Type RM Length L Ch R = 1 ,12690.05,370.498500,370.498500,370.498500
XS GIS Cut Line= 4
867337.649621097773807.293000047866388.309907095773400.758984707
866214.008645098773337.443753662865497.921970162773104.108466218
#Sta/Elev= 30
8875.37883.246518906.60683.04796 8943.5373.827358957.41274.895259095.82773.51815
 9204.6175.06403 9269.8873.680299346.02875.403669443.93374.326339490.87776.14837
9563.59474.993059607.10876.052549661.49974.59522  9932.976.031399954.25775.11492
9986.09768.063699996.73667.8505310007.38  70.55610018.0175.1647210028.6575.73198
10081.8575.0864910187.1677.4243110323.8976.8607110492.1778.32953 10513.278.94355
10534.2481.6360410639.4181.2514310702.5285.8870710786.6687.7259410846.6995.62778
#Mann= 3 , 0 , 0
8875.378  0.0673       08875.378  0.0673       010846.69  0.0673       0
#XS Ineff= 2 , 0
       09317.588        10035.51       0
Bank Sta=8875.378,10846.69
Exp/Cntr=0.3,0.1

Type RM Length L Ch R = 1 ,12319.55,103.373500,103.373500,103.373500
XS GIS Cut Line= 4
867380.963406548773823.440035359866505.531759542773069.292628215
866439.304856482773010.434761005865840.113250348 772563.55442306
#Sta/Elev= 30
8815.95391.704078837.02383.692868844.20682.41074 8876.6281.576778905.49371.81297
8920.81473.841378951.45774.604449087.80272.430449196.60373.843779380.46271.99894
9411.10573.26415 9589.3671.553869642.15666.506929671.572 71.36469840.13970.26342
9972.13872.553259985.516 70.78469998.89565.73703   1000866.2707510023.0572.22139
10053.1674.2591810127.77 74.829910152.7573.9247610169.4871.2517410190.1571.26327
10302.4274.5478410676.6775.6320510704.7378.0921610739.0476.9268210807.5179.93658
#Mann= 3 , 0 , 0
8815.953  0.0722       08815.953  0.0722       010807.51  0.0722       0
#XS Ineff= 2 , 0
       09425.818        10071.16       0
Bank Sta=8815.953,10807.51
Exp/Cntr=0.3,0.1

Type RM Length L Ch R = 3 ,12257.11,,,
BEGIN DESCRIPTION:
END DESCRIPTION:
Bridge Culvert--1,0,-1,-1, 0
Deck Dist Width WeirC Skew NumUp NumDn MinLoCord MaxHiCord MaxSubmerge Is_Ogee
31.186750,41.000000,2.6,0, 30, 30, , , 0.95, 0, 0,0,,
 9879.71 9880.65 9883.17 9894.85 9897.25 9909.05 9911.34 9923.24 9925.43 9937.44
 9939.51 9951.64 9953.60 9965.84 9967.69 9980.03 9981.78 9985.45 9985.45 9994.23
 9995.8610008.4310009.9510016.4510016.4510022.6310024.0410036.8210038.1210046.54
   70.46   70.45   70.43   70.38   70.35   70.49   70.54   70.61   70.64   71.06
   71.09   71.24   71.20   70.99   71.02   71.10   71.03   71.13   71.13   71.37
   71.51   71.82   71.85   71.77   71.77   71.69   71.69   71.83   71.80   71.56
 -929.54 -929.55 -929.57 -929.62 -929.65 -929.51 -929.46 -929.39 -929.36 -928.94
 -928.91 -928.76 -928.80 -929.01 -928.98 -928.90 -928.97 -928.87   68.63   68.87
   69.01   69.32   69.35   69.27 -928.23 -928.31 -928.31 -928.17 -928.20 -928.44
 9879.71 9880.65 9883.17 9894.85 9897.25 9909.05 9911.34 9923.24 9925.43 9937.44
 9939.51 9951.64 9953.60 9965.84 9967.69 9980.03 9981.78 9986.61 9986.61 9994.23
 9995.8610008.4310009.9510017.6110017.6110022.6310024.0410036.8210038.1210046.54
   70.46   70.45   70.43   70.38   70.35   70.49   70.54   70.61   70.64   71.06
   71.09   71.24   71.20   70.99   71.02   71.10   71.03   71.16   71.16   71.37
   71.51   71.82   71.85   71.75   71.75   71.69   71.69   71.83   71.80   71.56
 -929.54 -929.55 -929.57 -929.62 -929.65 -929.51 -929.46 -929.39 -929.36 -928.94
 -928.91 -928.76 -928.80 -929.01 -928.98 -928.90 -928.97 -928.84   68.66   68.87
   69.01   69.32   69.35   69.25 -928.25 -928.31 -928.31 -928.17 -928.20 -928.44
Pier Skew, UpSta & Num, DnSta & Num=  ,10000.95, 2 ,10002.11, 2 , 0 , 0 , 0 ,,
    2.00    2.00
 -928.37   71.63
    2.00    2.00
 -928.34   71.66
BR Coef=-1 , 0 , 0 ,, 0 ,,,0.8,0,1,0,
WSPro=,,,, 1 ,,,, 0 ,,,, 0 ,,,,-1 ,-1 ,-1 , 0 , 0 , 0 , 0 , 0
BC Design=,, 0 ,, 0 ,,,,,,

Type RM Length L Ch R = 1 ,12216.18,361.904700,361.904700,361.904700
XS GIS Cut Line= 4
867401.584526943773820.211017691866659.330761706773079.315287697
 866497.76870393772920.022517385865920.855580584772469.488832451
#Sta/Elev= 30
8793.48292.433528816.914 83.94088829.16881.150718857.47880.622528885.789 71.8873
8899.94473.264778999.02972.51604 9055.6573.593229197.20172.940119239.66671.31729
 9254.9272.806479381.21770.831299536.92371.361769636.009 67.37439650.53771.47122
9962.31969.911949974.69769.773379990.80661.9087510005.0561.4987210016.8362.29501
10030.87 71.112410033.5471.6109210123.3869.9595110272.2472.8032710337.2371.33745
 10467.274.2498810548.4473.6201710668.9675.6940910694.6674.27989 10801.178.57041
#Mann= 3 , 0 , 0
8793.482  0.0578       08793.482  0.0578       0 10801.1  0.0578       0
#XS Ineff= 2 , 0
       09428.725        10064.08       0
Bank Sta=8793.482,10801.1
Exp/Cntr=0.3,0.1

Type RM Length L Ch R = 1 ,11854.27,411.304200,411.304200,411.304200
XS GIS Cut Line= 2
867491.821122158773786.537749519 866232.83360167771825.500674317
#Sta/Elev= 30
8755.89393.566598793.37175.953038829.02173.611628840.90570.547338864.67272.47854
9007.27372.945749114.22472.264959126.10870.757169435.07869.70219 9527.4367.45065
9601.44669.240129619.98164.271979638.49167.497339922.29966.895839981.71665.70188
  9993.660.6202410005.4861.0175110029.2568.7610710230.8170.6931610243.1572.95538
10255.0470.8212610338.2271.6215510373.8769.4311910552.1266.8167310635.3169.54357
10766.0268.5076410884.8672.6530511003.69 71.166811063.1175.4745911086.2875.21528
#Mann= 3 , 0 , 0
8755.893  0.0592       08755.893  0.0592       011086.28  0.0592       0
#XS Ineff= 2 , 0
       09467.772        10200.67       0
Bank Sta=8755.893,11086.28
Exp/Cntr=0.3,0.1

Type RM Length L Ch R = 1 ,11442.97,145.842500,145.842500,145.842500
XS GIS Cut Line= 5
867628.129503438773736.554047538867262.429975646772819.129569796
867245.404992991772728.039037358866978.132018614771961.969386199
866516.103629567771699.634988278
#Sta/Elev= 30
8824.74892.75097  8833.291.167168847.95285.584078880.24770.445148923.30868.72785
8944.83971.352979049.25271.947699343.15168.701039762.99366.355349795.28966.84416
9867.44171.335489961.216 70.03639971.80766.720619982.39861.328559992.98958.15815
10003.5857.6162110024.7665.9506210045.9567.0317310331.91 66.962310353.0964.97078
10384.8664.7398610564.9166.5099410617.8765.18232   10692 68.916110771.0269.26859
10823.4967.7165710938.4969.3154811007.49  68.72411034.3171.1611911247.7172.15308
#Mann= 3 , 0 , 0
8824.748    0.06       08824.748    0.06       011247.71    0.06       0
#XS Ineff= 2 , 0
       09945.007        10044.95       0
Bank Sta=8824.748,11247.71
Exp/Cntr=0.3,0.1

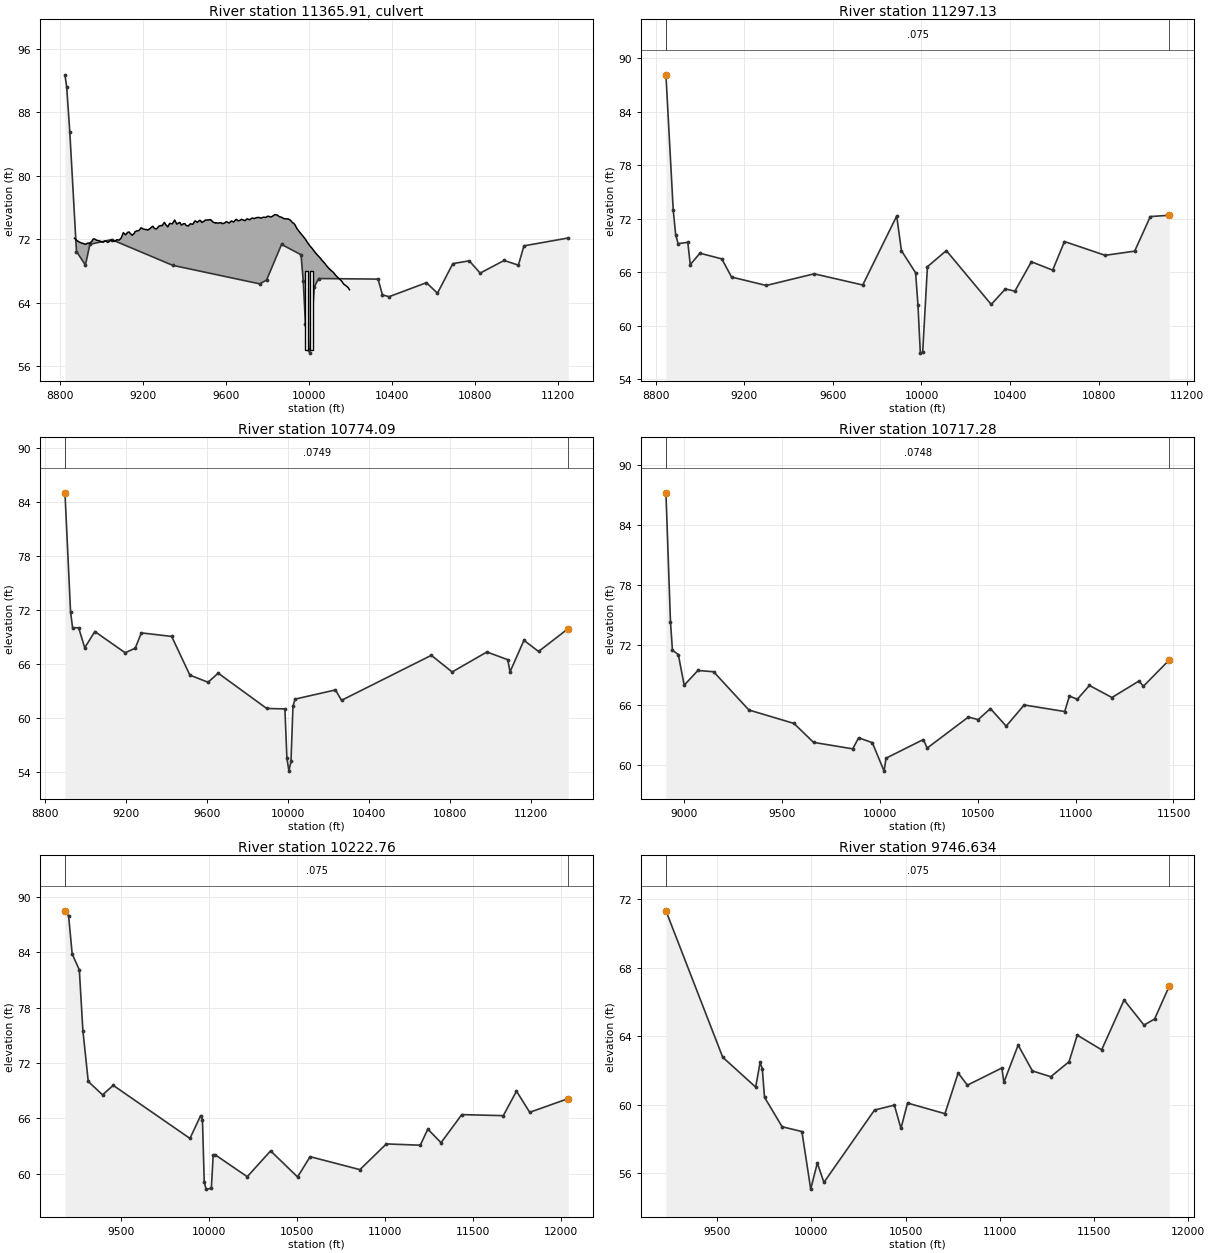
Type RM Length L Ch R = 2 ,11365.91,,,
Bridge Culvert--1,0,-1,-1, 0
Deck Dist Width WeirC Skew NumUp NumDn MinLoCord MaxHiCord MaxSubmerge Is_Ogee
29.921,86,2.6,0,176,176, , , 0.95, 0, 0,0,,
 8870.53 8871.00 8875.23 8881.67 8892.34 8903.01 8903.91 8913.68 8924.35 8932.60
 8935.02 8945.69 8956.36 8961.29 8967.03 8977.69 8988.36 8989.97 8999.03 9009.70
 9018.66 9020.37 9031.04 9041.71 9047.35 9052.38 9063.05 9073.72 9076.03 9084.39
 9095.06 9104.72 9105.73 9116.40 9127.06 9133.40 9137.73 9148.40 9159.07 9162.09
 9169.74 9180.41 9190.78 9191.08 9201.75 9212.42 9219.46 9223.09 9233.76 9244.43
 9248.15 9255.10 9265.76 9276.43 9276.84 9287.10 9292.80 9297.90 9303.77 9308.83
 9319.76 9328.50 9330.70 9341.63 9352.56 9353.24 9363.50 9374.43 9377.97 9385.36
 9396.30 9402.70 9407.23 9418.16 9427.43 9429.10 9440.03 9450.97 9452.17 9461.90
 9472.83 9476.90 9483.77 9494.70 9501.63 9505.63 9516.57 9526.37 9527.50 9538.43
 9549.37 9551.10 9560.30 9571.23 9575.83 9582.17 9593.10 9600.56 9604.03 9614.97
 9625.30 9625.90 9636.84 9647.77 9650.03 9657.39 9658.71 9669.75 9674.01 9680.78
 9691.81 9697.68 9702.85 9713.88 9721.35 9724.91 9735.95 9745.01 9746.98 9758.01
 9768.68 9769.05 9780.08 9791.11 9792.35 9802.15 9813.18 9816.02 9824.15 9824.21
 9834.93 9842.35 9845.65 9856.38 9867.10 9870.07 9877.82 9888.54 9897.80 9899.26
 9909.99 9920.71 9925.52 9928.48 9931.30 9941.54 9951.79 9962.04 9969.49 9972.28
 9982.53 9992.7710003.0210013.2710015.4010023.5110033.7610044.0010054.2510061.31
10064.5010074.7410084.9910095.2310105.4810107.2210115.7310125.9710136.2210146.46
10153.1310156.7110166.9610177.2010187.4510194.42
   72.12   72.11   72.00   71.84   71.66   71.53   71.52   71.45   71.35   71.48
   71.50   71.52   71.81   72.03   72.03   71.86   71.80   71.82   71.67   71.63
   71.78   71.78   71.59   71.77   71.88   71.85   71.72   71.89   71.94   71.87
   72.13   72.79   72.82   72.55   72.87   72.91   72.77   72.49   72.77   72.95
   73.04   73.09   73.44   73.44   73.28   73.22   73.22   73.15   73.33   73.59
   73.63   73.36   73.30   73.63   73.64   73.73   73.70   73.93   74.12   73.87
   73.57   73.98   73.99   73.94   74.41   74.40   73.90   74.10   74.11   73.77
   73.97   73.95   73.76   73.66   73.93   73.94   73.88   74.31   74.31   74.13
   74.38   74.35   74.12   74.28   74.43   74.41   74.44   74.47   74.42   74.15
   74.04   74.08   74.03   74.08   74.08   73.96   74.04   74.20   74.19   74.04
   74.29   74.30   74.17   74.49   74.50   74.33   74.31   74.42   74.51   74.45
   74.34   74.50   74.57   74.45   74.61   74.67   74.61   74.69   74.72   74.75
   74.66   74.66   74.78   74.75   74.77   74.91   74.82   74.80   74.91   74.91
   75.10   75.07   75.07   74.85   74.77   74.73   74.60   74.57   74.55   74.56
   74.40   74.07   74.01   73.93   73.85   73.34   72.98   72.66   72.43   72.33
   71.98   71.56   71.18   70.87   70.81   70.52   70.18   69.90   69.60   69.37
   69.26   68.97   68.62   68.31   68.06   68.02   67.84   67.50   67.21   66.98
   66.80   66.71   66.32   66.13   65.90   65.62
                                                                                
                                                                                
                                                                                
                                                                                
                                                                                
                                                                                
                                                                                
                                                                                
                                                                                
                                                                                
                                                                                
                                                                                
                                                                                
                                                                                
                                                                                
                                                                                
                                                                                
                                                
 8870.53 8871.00 8875.23 8881.67 8892.34 8903.01 8903.91 8913.68 8924.35 8932.60
 8935.02 8945.69 8956.36 8961.29 8967.03 8977.69 8988.36 8989.97 8999.03 9009.70
 9018.66 9020.37 9031.04 9041.71 9047.35 9052.38 9063.05 9073.72 9076.03 9084.39
 9095.06 9104.72 9105.73 9116.40 9127.06 9133.40 9137.73 9148.40 9159.07 9162.09
 9169.74 9180.41 9190.78 9191.08 9201.75 9212.42 9219.46 9223.09 9233.76 9244.43
 9248.15 9255.10 9265.76 9276.43 9276.84 9287.10 9292.80 9297.90 9303.77 9308.83
 9319.76 9328.50 9330.70 9341.63 9352.56 9353.24 9363.50 9374.43 9377.97 9385.36
 9396.30 9402.70 9407.23 9418.16 9427.43 9429.10 9440.03 9450.97 9452.17 9461.90
 9472.83 9476.90 9483.77 9494.70 9501.63 9505.63 9516.57 9526.37 9527.50 9538.43
 9549.37 9551.10 9560.30 9571.23 9575.83 9582.17 9593.10 9600.56 9604.03 9614.97
 9625.30 9625.90 9636.84 9647.77 9650.03 9657.39 9658.71 9669.75 9674.01 9680.78
 9691.81 9697.68 9702.85 9713.88 9721.35 9724.91 9735.95 9745.01 9746.98 9758.01
 9768.68 9769.05 9780.08 9791.11 9792.35 9802.15 9813.18 9816.02 9824.15 9824.21
 9834.93 9842.35 9845.65 9856.38 9867.10 9870.07 9877.82 9888.54 9897.80 9899.26
 9909.99 9920.71 9925.52 9928.48 9931.30 9941.54 9951.79 9962.04 9969.49 9972.28
 9982.53 9992.7710003.0210013.2710015.4010023.5110033.7610044.0010054.2510061.31
10064.5010074.7410084.9910095.2310105.4810107.2210115.7310125.9710136.2210146.46
10153.1310156.7110166.9610177.2010187.4510194.42
   72.12   72.11   72.00   71.84   71.66   71.53   71.52   71.45   71.35   71.48
   71.50   71.52   71.81   72.03   72.03   71.86   71.80   71.82   71.67   71.63
   71.78   71.78   71.59   71.77   71.88   71.85   71.72   71.89   71.94   71.87
   72.13   72.79   72.82   72.55   72.87   72.91   72.77   72.49   72.77   72.95
   73.04   73.09   73.44   73.44   73.28   73.22   73.22   73.15   73.33   73.59
   73.63   73.36   73.30   73.63   73.64   73.73   73.70   73.93   74.12   73.87
   73.57   73.98   73.99   73.94   74.41   74.40   73.90   74.10   74.11   73.77
   73.97   73.95   73.76   73.66   73.93   73.94   73.88   74.31   74.31   74.13
   74.38   74.35   74.12   74.28   74.43   74.41   74.44   74.47   74.42   74.15
   74.04   74.08   74.03   74.08   74.08   73.96   74.04   74.20   74.19   74.04
   74.29   74.30   74.17   74.49   74.50   74.33   74.31   74.42   74.51   74.45
   74.34   74.50   74.57   74.45   74.61   74.67   74.61   74.69   74.72   74.75
   74.66   74.66   74.78   74.75   74.77   74.91   74.82   74.80   74.91   74.91
   75.10   75.07   75.07   74.85   74.77   74.73   74.60   74.57   74.55   74.56
   74.40   74.07   74.01   73.93   73.85   73.34   72.98   72.66   72.43   72.33
   71.98   71.56   71.18   70.87   70.81   70.52   70.18   69.90   69.60   69.37
   69.26   68.97   68.62   68.31   68.06   68.02   67.84   67.50   67.21   66.98
   66.80   66.71   66.32   66.13   65.90   65.62
                                                                                
                                                                                
                                                                                
                                                                                
                                                                                
                                                                                
                                                                                
                                                                                
                                                                                
                                                                                
                                                                                
                                                                                
                                                                                
                                                                                
                                                                                
                                                                                
                                                                                
                                                
BR Coef=-1 , 0 , 0 ,, 0 ,,,0.8,-1,,0,
WSPro=,,,, 1 ,,,, 0 ,,,, 0 ,,,,-1 ,-1 ,-1 , 0 , 0 , 0 , 0 , 0
Multiple Barrel Culv=2,10,13,86,0.013,0.5,1,8,3,58,57,2,Culvert #1, 0, 29.921
 9987.00 9987.0010013.0010013.00
Culvert Bottom n=0.013
BC Design=,, 0 ,, 0 ,,,,,,

Type RM Length L Ch R = 1 ,11297.13,523.035700,523.035700,523.035700
XS GIS Cut Line= 4
867820.856429404773655.060984302867396.044487095772711.316737989
 867127.80389094771988.710260805866732.562240182771741.358569024
#Sta/Elev= 30
8846.52688.121728879.49272.944698890.45870.215378901.425 69.1902 8945.2969.34116
8956.25766.835939000.12268.11691 9098.8267.481219142.68665.445999299.319 64.4998
9515.54465.808269734.87264.554499888.21272.286869909.54668.399759973.54665.92473
9984.21362.29866 9994.88 56.913410005.5557.0246510026.8866.6056910112.2168.40833
10314.8862.3737210378.8864.1135210421.5563.8607210496.22 67.159610592.2266.21912
10645.5569.4267110828.91 67.880410962.2968.3511711033.0772.2291811118.5272.37243
#Mann= 3 , 0 , 0
8846.526   0.075       08846.526   0.075       011118.52   0.075       0
#XS Ineff= 2 , 0
       09949.608        10054.88       0
Bank Sta=8846.526,11118.52
Exp/Cntr=0.3,0.1

Type RM Length L Ch R = 1 ,10774.09,56.815000,56.815000,56.815000
XS GIS Cut Line= 4
867871.097118476773632.757127864867876.312780847772851.208138223
867866.636581773772040.272022458867083.390850565771603.405313789
#Sta/Elev= 30
 8897.0184.984418924.76871.747978934.768 70.01198964.76870.002548994.76967.78621
 9044.7769.589489194.77467.231049244.77567.741779274.77569.437269424.77969.04356
9514.78164.752429604.78363.955689654.78464.96792  9894.8 61.04799984.80660.99741
9994.80755.5028410004.8154.0916910014.8155.1834210024.8161.2966410034.8162.08604
10234.82 63.104510264.8361.95242   1070966.9459610812.0565.0995210983.8167.31826
11086.8666.4620511098.3165.1156911167.0168.6122511239.4467.3746811386.4169.91897
#Mann= 3 , 0 , 0
 8897.01  0.0749       0 8897.01  0.0749       011386.41  0.0749       0
#XS Ineff= 2 , 0
       09852.385        10416.51       0
Bank Sta=8897.01,11386.41
Exp/Cntr=0.3,0.1

Type RM Length L Ch R = 1 ,10717.28,494.515200,494.515200,494.515200
XS GIS Cut Line= 4
 867930.55324729773618.193086758867932.451432859772718.124642137
867920.393501253772003.134886476867090.220408482771534.536090153
#Sta/Elev= 30
 8909.9687.213238933.15374.309758943.15371.477468973.15371.038969003.153 67.9763
9073.15369.446949153.15369.321919333.15465.498419563.15464.152939663.15462.25924
9863.162 61.60959893.16662.715339963.176  62.23110023.1859.3822210033.1960.67862
10223.2162.5383610243.2261.6878810453.2564.7931510503.2564.5328410565.7665.63629
10646.1563.8821710738.0165.9989710944.7165.3439710968.8866.8837111009.5766.57609
11071.0267.9514711185.8566.7432111323.6568.3908111346.6167.8758311478.4270.49987
#Mann= 3 , 0 , 0
 8909.96  0.0748       0 8909.96  0.0748       011478.42  0.0748       0
#XS Ineff= 2 , 0
       09822.481        10441.23       0
Bank Sta=8909.96,11478.42
Exp/Cntr=0.3,0.1

Type RM Length L Ch R = 1 ,10222.76,476.126100,476.126100,476.126100
XS GIS Cut Line= 6
868546.004979606773435.523213964868409.201929078772629.376738564
868408.922685267772627.396328764868402.512650147772587.380628787
868241.085325826771804.751936581867120.469168406771370.607869813
#Sta/Elev= 30
9181.32888.466539202.14587.900159222.43183.794969263.00382.083939283.28975.51093
9313.71770.007339394.86168.560479455.71969.585969891.86763.844259952.72466.31326
9962.86765.88458 9973.0159.157849983.153 58.358510013.5558.4327510023.6862.00567
10033.8162.0912510217.5459.7032910350.2762.4985210503.4359.67671 10574.961.87077
10857.8860.4678711008.0263.2489311201.0563.1112611243.9564.8497411319.02 63.3823
11436.9966.4202111672.9266.3079911747.9968.9589911823.0666.67096 12042.468.15396
#Mann= 3 , 0 , 0
9181.328   0.075       09181.328   0.075       0 12042.4   0.075       0
#XS Ineff= 2 , 0
       09947.473        10594.27       0
Bank Sta=9181.328,12042.4
Exp/Cntr=0.3,0.1

Type RM Length L Ch R = 1 ,9746.634,102.194400,102.194400,102.194400
XS GIS Cut Line= 3
869210.828048622773042.962373119868360.717575568771632.772884989
867413.107520828771244.149626437
#Sta/Elev= 30
9228.28971.312289529.49962.768329704.44261.02398    972862.461979739.67662.09461
9751.35360.431629844.76558.709339949.854 58.4278 9996.5655.0670510031.5956.59164
10066.6255.4606410335.1859.6837810440.4859.96945 10475.358.6111910510.3360.09147
10708.8359.4709110778.89 61.842810827.86 61.136211010.7862.1388411021.5961.30311
11097.2463.47724 11172.961.9674111270.1861.6279611367.4562.5059911410.6864.05748
11540.3863.1995711659.2766.1085611765.0964.64218 11821.465.00122 11899.166.92004
#Mann= 3 , 0 , 0
9228.289   0.075       09228.289   0.075       0 11899.1   0.075       0
#XS Ineff= 2 , 0
       09907.991        10375.87       0
Bank Sta=9228.289,11899.1
Exp/Cntr=0.3,0.1

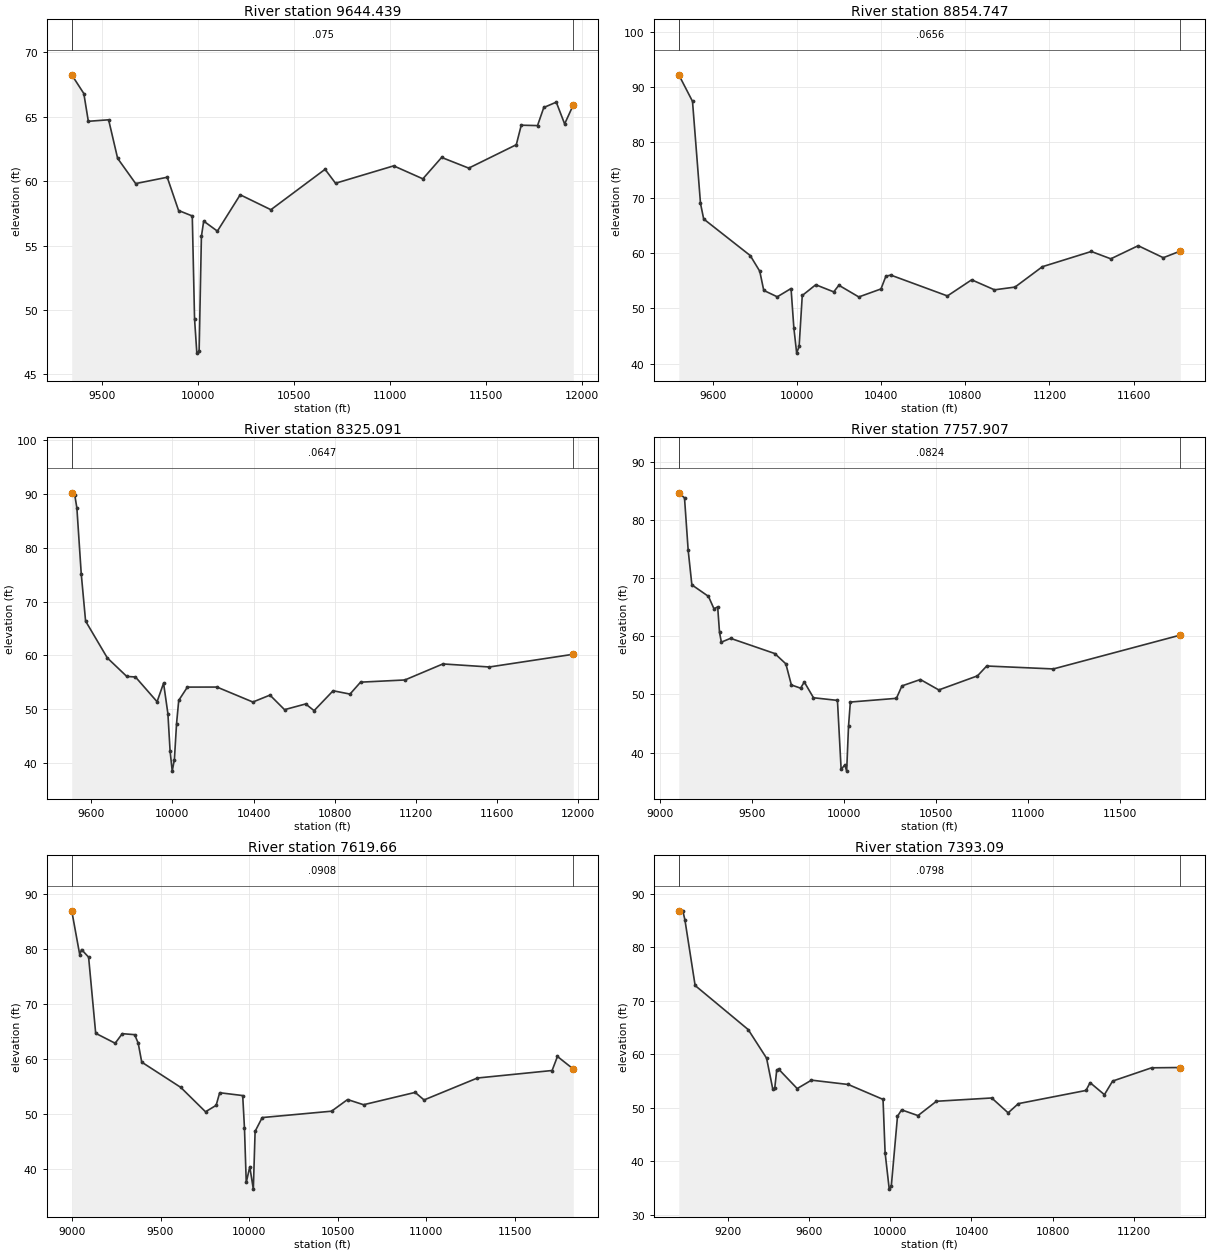
Type RM Length L Ch R = 1 ,9644.439,789.692600,789.692600,789.692600
XS GIS Cut Line= 5
869254.184311556772908.607399656868982.144491741772464.758964397
 868794.99282075772172.985827879868392.325752141771532.264613896
867483.556877843771150.066949626
#Sta/Elev= 30
9342.78668.252749405.66266.801319429.11964.646639534.67964.763869581.59461.77075
9675.42559.813629839.62960.305429898.72457.724849970.00757.300839981.88749.31111
9993.767 46.657810005.65 46.789910017.5355.7116310029.41 56.901310100.6956.12474
10219.4458.9440210379.1357.7857310661.0360.9216210715.4959.8394711018.0961.18943
11169.9760.1831411267.6161.8429711408.64 61.013211656.1562.8295611681.9564.34437
11766.6364.3137911799.18 65.717511864.2766.1323811907.6664.4420911952.6265.91266
#Mann= 3 , 0 , 0
9342.786   0.075       09342.786   0.075       011952.62   0.075       0
#XS Ineff= 2 , 0
       09882.453        10373.51       0
Bank Sta=9342.786,11952.62
Exp/Cntr=0.3,0.1

Type RM Length L Ch R = 1 ,8854.747,529.655400,529.655400,529.655400
XS GIS Cut Line= 6
870033.161096983772583.855635479869941.831279803 772480.20300052
869636.041876153772113.082715931869524.174353187771954.723981204
869045.473144685771663.767140385868110.258283598771271.074428279
#Sta/Elev= 30
9437.96392.179269503.07787.391089541.06568.968769556.19266.156899777.55959.55506
9822.82756.728849841.794 53.26679906.02952.107559971.58653.604269984.92746.50723
9998.27641.9418410009.9343.1496810024.89 52.3446   10089 54.283710174.5552.99758
10198.8854.1962410293.7352.0835710399.0553.5241510422.4555.8279210445.8656.02748
10715.0152.2661610830.2855.1757410938.7453.3692511036.3553.86389 11166.557.54326
11398.9760.2889111491.8758.9682811622.0261.3341711741.3259.1681811822.3960.36419
#Mann= 3 , 0 , 0
9437.963  0.0656       09437.963  0.0656       011822.39  0.0656       0
#XS Ineff= 2 , 0
       09940.512        10798.43       0
Bank Sta=9437.963,11822.39
Exp/Cntr=0.3,0.1

Type RM Length L Ch R = 1 ,8325.091,567.184100,567.184100,567.184100
XS GIS Cut Line= 6
870438.632357845 771897.59676273870297.795240012771843.185809398
 869975.32163663771724.007353239869973.449806634771723.302901324
869899.467412205771695.672300084868077.581257954771172.547976398
#Sta/Elev= 30
9504.22690.19641 9518.8489.863879529.56187.371079551.00175.172569572.44266.38305
 9679.5159.54195 9775.4656.098669818.10556.003999924.71551.404729956.69954.85007
9978.02149.193389988.68242.343389999.34438.5173510010.0240.6720510020.6947.32769
10031.3751.6495710074.07 54.120910219.8754.1274910396.7451.3494910480.9952.63506
 10552.849.9317910656.8550.9905110698.3949.74708 10792.153.4423410875.3352.82494
10927.3555.0372311145.8455.4445311333.1158.42352   1156257.8563911975.4860.21922
#Mann= 3 , 0 , 0
9504.226  0.0647       09504.226  0.0647       011975.48  0.0647       0
#XS Ineff= 2 , 0
       09913.321        10853.55       0
Bank Sta=9504.226,11975.48
Exp/Cntr=0.3,0.1

Type RM Length L Ch R = 1 ,7757.907,138.247400,138.247400,138.247400
XS GIS Cut Line= 3
870805.870456979771146.084815309 869114.87200668771211.910683142
868088.872731171771106.290398784
#Sta/Elev= 30
9103.333 84.61819134.22783.754049154.24274.731539174.25868.804739264.32666.82818
9294.34864.693829314.36465.020949324.37160.644739334.37958.964719384.41759.61904
9624.59857.005289684.644 55.23599714.667 51.61149764.70451.05739 9784.7252.11837
9834.75749.410749964.85648.956739984.871 37.094310004.8937.8777110014.89 36.8041
 10024.944.4760910034.9148.67392 10285.149.3110110315.1251.44616 10415.252.54399
10515.2750.7535810725.4353.1736110775.4754.8655911137.2854.3611111827.0360.17809
#Mann= 3 , 0 , 0
9103.333  0.0824       09103.333  0.0824       011827.03  0.0824       0
#XS Ineff= 2 , 0
       09914.595        10686.22       0
Bank Sta=9103.333,11827.03
Exp/Cntr=0.3,0.1

Type RM Length L Ch R = 1 , 7619.66,226.569900,226.569900,226.569900
XS GIS Cut Line= 6
870910.200723387771038.669725694 869949.00621783771043.838507356
869899.983341635771043.005488389869867.539116709771042.719706407
869811.253725379771039.304042462 868085.99675201770881.565486248
#Sta/Elev= 30
8998.56886.944899043.76978.94449 9053.77 79.8918 9093.7778.510489133.77164.64537
9243.77262.833429283.77364.576599353.77464.395949373.77462.855279393.774 59.3917
9613.77854.80441 9753.7850.355489813.78151.526439833.78153.823539963.78353.30897
9973.78547.366459983.78637.4911810003.7940.3215510023.7936.2709510033.79 46.7934
10073.8549.3017210465.4250.46121 10555.852.5822310646.1751.6386110937.3853.88351
10987.5952.5103411288.8456.5036211710.5957.8693911740.7260.4253311830.0958.14175
#Mann= 3 , 0 , 0
8998.568  0.0908       08998.568  0.0908       011830.09  0.0908       0
#XS Ineff= 2 , 0
       09951.973        10670.68       0
Bank Sta=8998.568,11830.09
Exp/Cntr=0.3,0.1

Type RM Length L Ch R = 1 , 7393.09,91.545800,91.545800,91.545800
XS GIS Cut Line= 6
870974.937771273770927.348138582870029.141373989770835.978390059
869935.054796647770819.270152032869933.087042366770818.912471529
869903.152463289770813.344312975868524.444548435770634.361938272
#Sta/Elev= 30
8959.46286.846288979.49286.783148989.53985.146559039.772 72.88349300.98264.64149
9391.40159.298719421.54153.597979431.58753.659449441.63457.13434 9451.6857.20825
9542.09953.609949612.42555.184689793.26354.37509 9964.6551.586689974.806 41.6199
9995.11934.8072210005.2835.3580410035.7948.4297510055.9749.6303410136.6448.55712
 10227.451.2353510499.66 51.851710580.3449.0725610630.7650.7930410963.5253.26002
10983.6954.7180811054.2852.4716711094.6255.0132411286.2157.4909311427.9457.54987
#Mann= 3 , 0 , 0
8959.462  0.0798       08959.462  0.0798       011427.94  0.0798       0
#XS Ineff= 2 , 0
       09946.151        10659.31       0
Bank Sta=8959.462,11427.94
Exp/Cntr=0.3,0.1