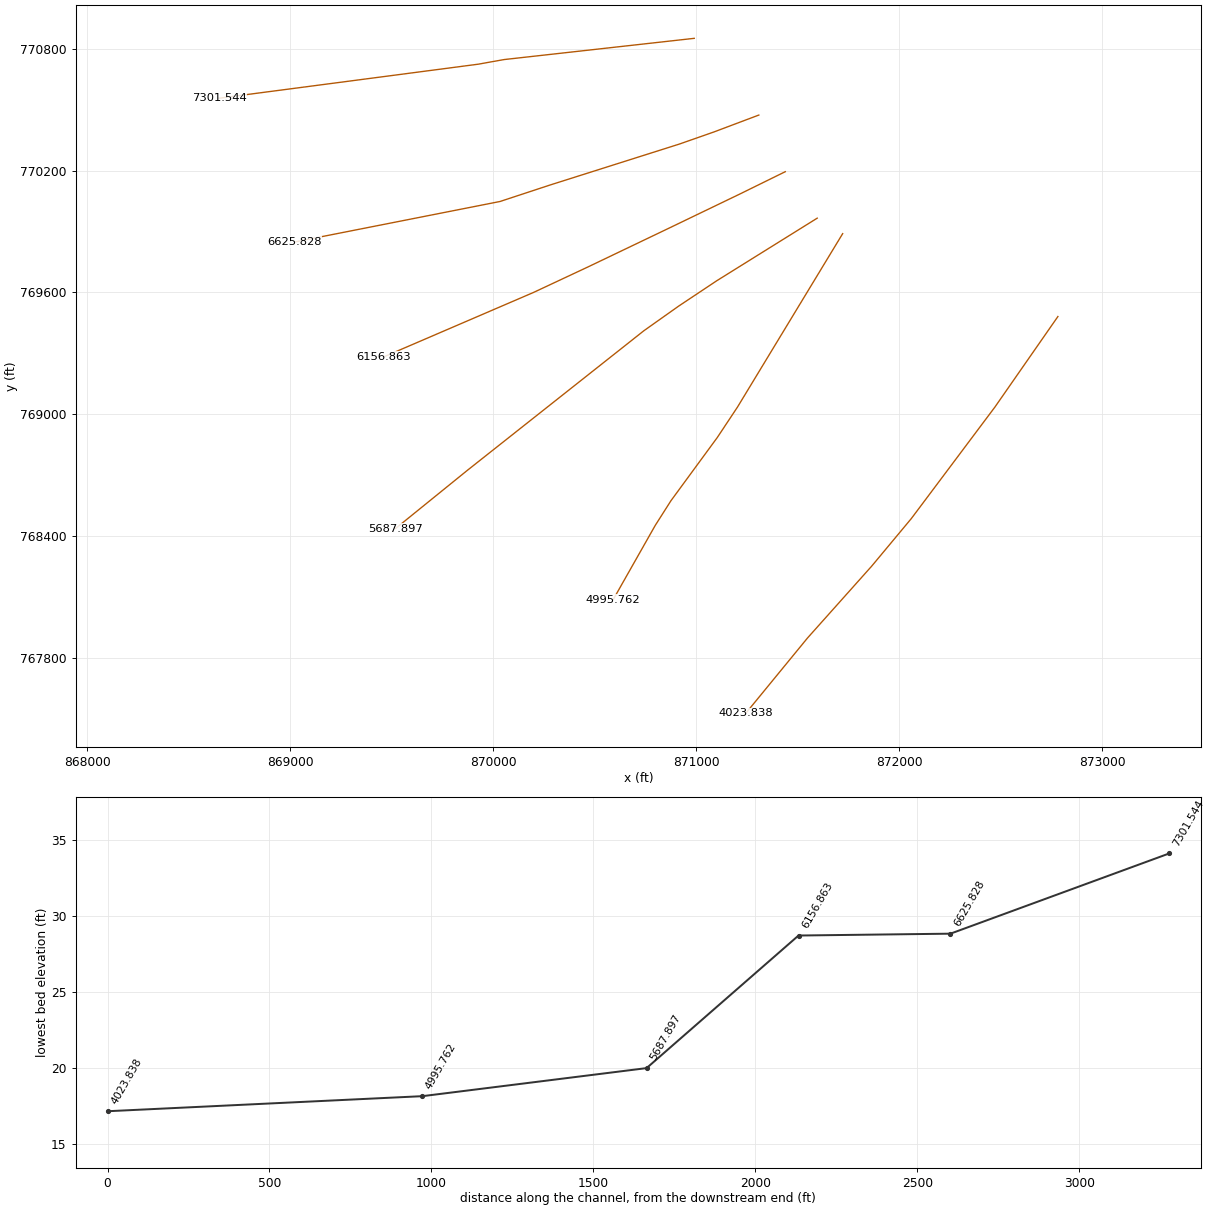
HEC-RAS study 9816_ras.prj: 9816

--- 9816_ras.g01 (geometry) --- (continued)

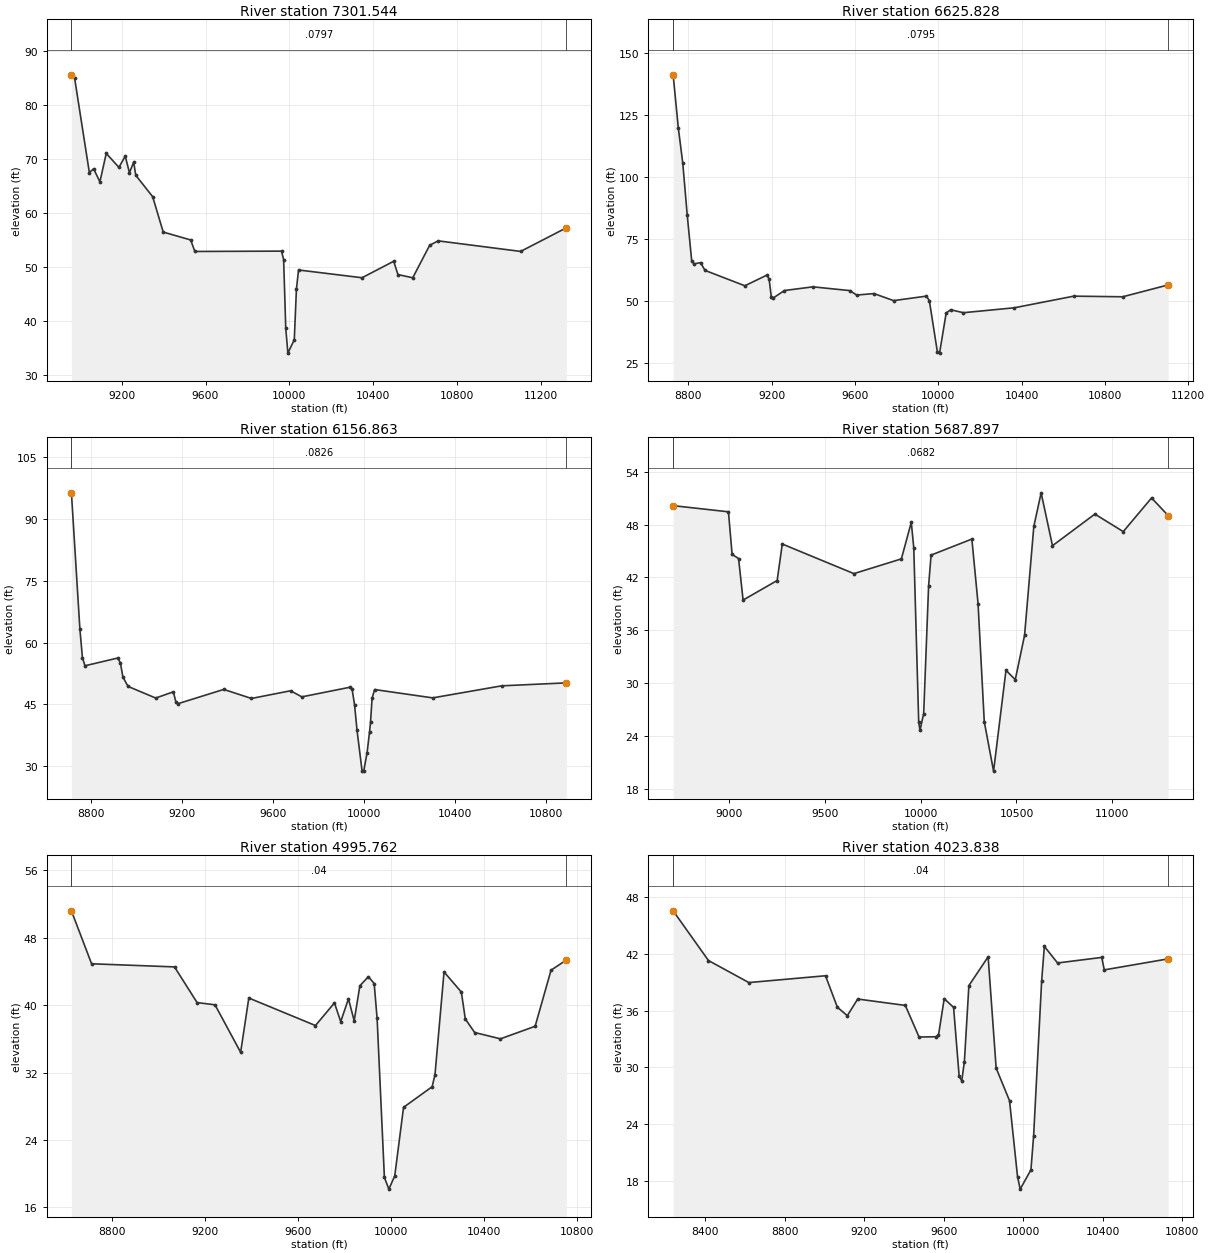
Type RM Length L Ch R = 1 ,7301.544,675.716100,675.716100,675.716100
XS GIS Cut Line= 6
870990.045113908770851.945345748870054.193371502770747.486297051
869960.106669573770730.777999405 869958.13891269770730.420317582
869928.204294068770724.852139717868648.475288747770556.861744425
#Sta/Elev= 30
8960.436  85.5398975.57584.964849046.009 67.47839066.13368.18398 9096.3265.77046
9126.50671.020929186.87968.443199217.06570.514749237.18967.456069257.31369.41331
9267.37566.973869347.87263.023919398.18356.48911 9528.9955.033839549.11452.90425
9962.21952.968569972.37551.414639982.53238.713919992.68834.1231310023.1936.60769
10033.3445.9283110043.4249.48581   1034648.0498410497.2851.0937210517.4648.63689
10588.0648.0446210668.7454.0520810709.0954.8648811102.4352.9140911320.8157.28091
#Mann= 3 , 0 , 0
8960.436  0.0797       08960.436  0.0797       011320.81  0.0797       0
#XS Ineff= 2 , 0
       09947.231         10654.6       0
Bank Sta=8960.436,11320.81
Exp/Cntr=0.3,0.1

Type RM Length L Ch R = 1 ,6625.828,468.965600,468.965600,468.965600
XS GIS Cut Line= 6
871308.211376288770473.973181068871086.355520089770390.451527598
870916.763382382770331.068160928870278.576701002 770128.96565181
  870033.2513907770048.185040034869020.462996814769848.439626603
#Sta/Elev= 30
8726.595141.30628751.397119.86148772.767105.61958794.13784.662478815.50866.27513
8826.19364.923458858.24865.409978879.61962.278339070.92556.071229176.75960.37674
 9187.2858.792949197.80151.587829208.32251.195739260.92854.146459397.703 55.6334
9575.75254.112399607.15752.313369690.90652.910149785.12250.067789942.55951.88365
9956.75650.077569995.20329.3995610005.7628.84977 10037.545.0433810058.6546.38148
10120.2645.1830110364.8847.1745710650.2851.8755210884.71 51.617911103.3856.40791
#Mann= 3 , 0 , 0
8726.595  0.0795       08726.595  0.0795       011103.38  0.0795       0
#XS Ineff= 2 , 0
       09909.633         10251.5       0
Bank Sta=8726.595,11103.38
Exp/Cntr=0.3,0.1

Type RM Length L Ch R = 1 ,6156.863,468.965600,468.965600,468.965600
XS GIS Cut Line= 6
871438.506208463770194.949015765871212.598325846770083.918056057
870858.995894587769913.603168747870463.889905266769724.483414758
870198.087072361769599.984702267869459.694374211769282.356073863
#Sta/Elev= 30
8711.92696.391578749.26163.251598760.40356.332448771.54654.345818916.39956.23442
8927.54155.033358938.68451.619968960.96949.333769083.07446.497629160.77148.01106
 9171.8745.55819 9182.9745.15569 9382.7348.595519504.68246.393819677.15748.26946
9726.41246.781689936.44149.102199947.47948.757049958.51844.904259969.55738.66239
9991.63428.82328    999928.7282310013.7233.1664710024.7738.3403110028.9640.60897
10035.82 46.450210046.8848.5649110302.7546.5364410606.4249.4675110891.4950.18748
#Mann= 3 , 0 , 0
8711.926  0.0826       08711.926  0.0826       010891.49  0.0826       0
#XS Ineff= 2 , 0
       0 9911.69         10086.3       0
Bank Sta=8711.926,10891.49
Exp/Cntr=0.3,0.1

Type RM Length L Ch R = 1 ,5687.897,692.134800,692.134800,692.134800
XS GIS Cut Line= 6
871595.894897766769966.050552708871100.686420441769657.526082251
 870914.09095825769533.316421986870742.394573676769411.793875191
869872.517549901 768723.85792634869518.023145657768436.801661101
#Sta/Elev= 30
  8708.450.144128996.96349.445699016.06744.610819049.80544.143169073.42939.42997
9251.20441.649579277.945 45.78929651.58942.431269899.46344.102649951.14948.25176
 9964.0745.373829989.91325.559369996.63824.64904 10015.826.5448110041.5941.06061
10054.4844.5337610267.2846.3527410299.6539.0064810332.0125.6325610380.5520.01756
10445.2831.4588910493.8230.3969410542.3635.4377910590.6447.78855 10628.8 51.5995
   1068845.6005410909.2349.1866911057.32 47.198511205.0351.0188211291.6249.02286
#Mann= 3 , 0 , 0
  8708.4  0.0682       0  8708.4  0.0682       011291.62  0.0682       0
#XS Ineff= 2 , 0
       09934.652        10103.97       0
Bank Sta=8708.4,11291.62
Exp/Cntr=0.3,0.1

Type RM Length L Ch R = 1 ,4995.762,971.924600,971.924600,971.924600
XS GIS Cut Line= 6
871721.242529385 769889.74423438871203.366419422769035.834654961
871103.885854972768885.831030231870875.472058055768574.286114398
870798.289796719768453.108077837870590.752351322768086.938627879
#Sta/Elev= 30
8624.83151.210578711.621 44.92479068.35844.554049165.52340.319219242.63940.05288
9352.90734.416349388.09240.859749674.89837.594419756.56740.283819783.45738.06098
9816.86140.764079841.40938.155819865.95842.31988 9902.7843.397779927.45242.57933
9940.09838.433069971.42119.564419990.68218.1743910015.9719.7464210053.8227.88339
10176.9130.33214 10189.131.7675910228.0743.9563910302.5341.5680410319.5438.37323
10359.8436.7651110470.6836.01609   1062037.50598 10688.444.1643810754.5845.37278
#Mann= 3 , 0 , 0
8624.831    0.04       08624.831    0.04       010754.58    0.04       0
#XS Ineff= 2 , 0
       09897.354        10221.52       0
Bank Sta=8624.831,10754.58
Exp/Cntr=0.3,0.1

Type RM Length L Ch R = 1 ,4023.838,0.000000,0.000000,0.000000
XS GIS Cut Line= 6
872781.584844405769481.362860455872470.285894421769034.057634409
872059.502358326768486.151406193 871864.60996658768252.162082157
871548.111489587767897.761139339871243.599968502767526.334463735
#Sta/Elev= 30
8239.29946.504678416.94441.269288620.08238.947069005.63639.663919065.398 36.3458
9115.43435.458189167.564 37.21219407.08736.539669476.26233.208669560.99633.23987
9573.90633.393389602.75837.247319649.83336.334349677.93329.080779691.07928.58965
9704.22430.627399726.86438.625849823.65641.662099863.99729.936779931.23326.50291
9971.57418.491389985.02217.1842610038.9819.2238710052.47 22.795910092.9739.15545
10106.4742.7580810172.9541.0122210395.0141.5958610407.9440.2824410729.1541.44408
#Mann= 3 , 0 , 0
8239.299    0.04       08239.299    0.04       010729.15    0.04       0
#XS Ineff= 2 , 0
       0  9799.8        10120.35       0
Bank Sta=8239.299,10729.15
Exp/Cntr=0.3,0.1